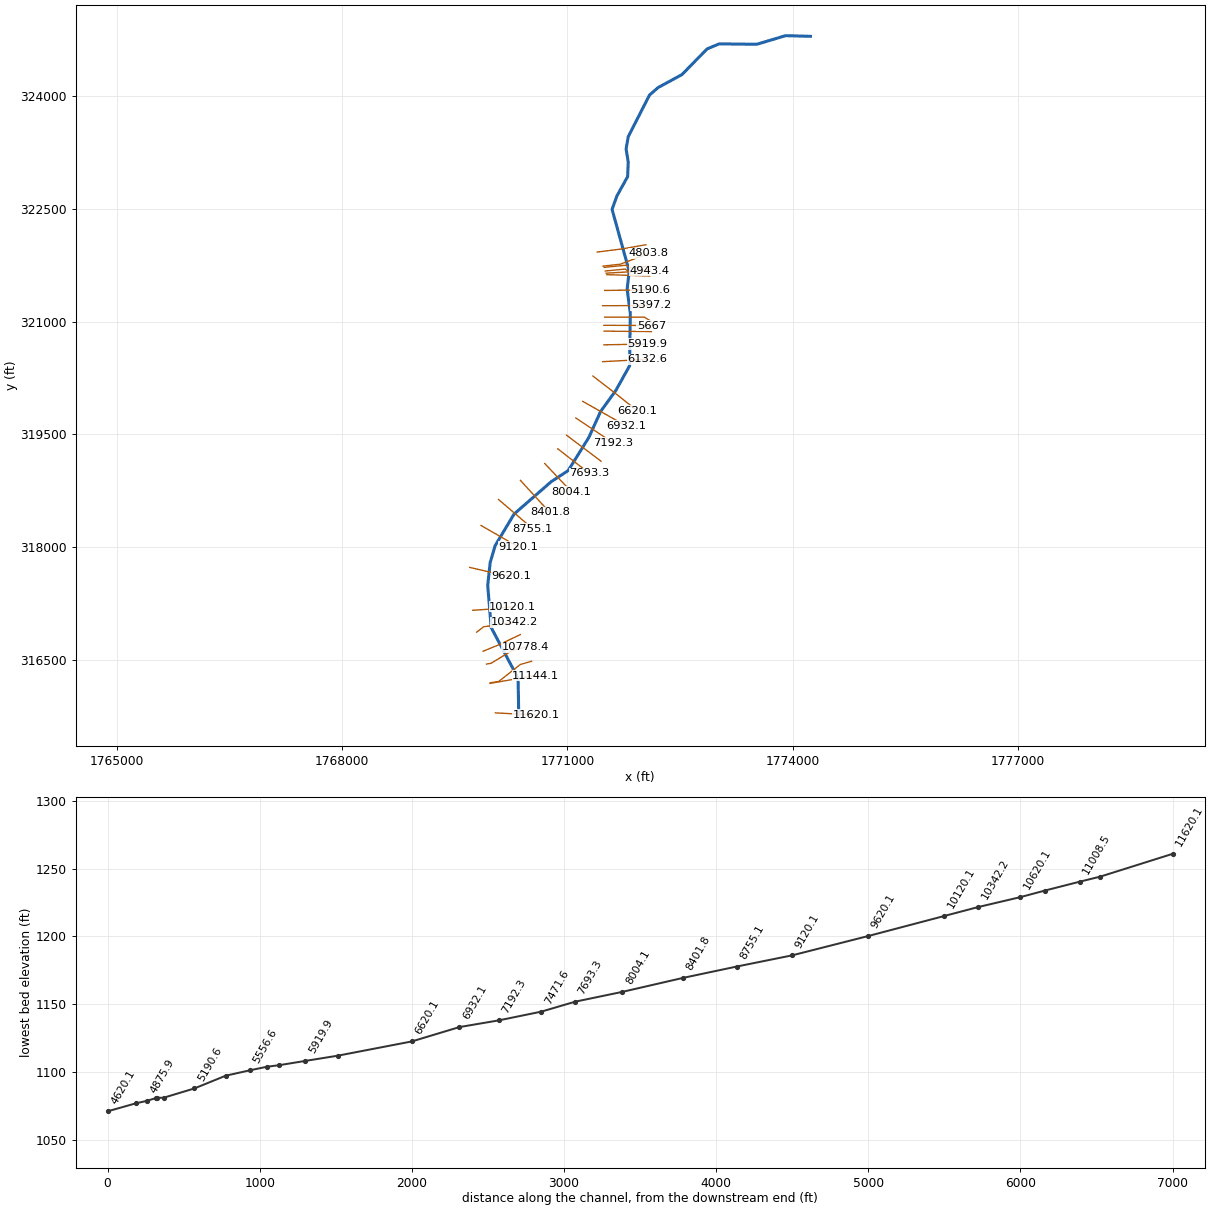
--- COWCK.prj (project) ---

Proj Title=COWCK
Current Plan=p01
Default Exp/Contr=0,0
English Units
Geom File=g01
Flow File=f01
Plan File=p01
BEGIN DESCRIPTION:
END DESCRIPTION:
DSS Export Rating Curves= 0
DSS Export Rating Curve Sorted= 0
DSS Export Volume Flow Curves= 0
DXF OffsetX= 0
DXF OffsetY= 0
DXF ScaleX= 0
DXF ScaleY= 0

--- COWCK.p01 (plan) ---

Plan Title=Floodplain
Program Version=4.00
Geom File=g01
Flow File=f01
K Sum by GR=0
Std Step Tol=0.01
Critical Tol=0.01
Num of Std Step Trials=20
Max Error Tol=0.3
Flow Tol Ratio=0.001
Split Flow NTrial=30
Split Flow Tol=0.02
Split Flow Ratio=0.02
Log Output Level=0
Friction Slope Method=1
Unsteady Friction Slope Method=2
Unsteady Bridges Friction Slope Method=1
Global Log Level=0
CheckData=False
Run HTab=0
Run UNet=0
Run PostProcess=0
UNET Theta=0
UNET Theta Warmup=0
UNET ZTol=0
UNET ZSATol=0
UNET MxIter=0
UNET MaxInSteps=0
UNET DtIC=0
UNET DtMin=0
UNET MaxCRTS=0
UNET WFStab=0
UNET SFStab=0
UNET WFX=0
UNET SFX=0
UNET DSS MLevel=0
UNET DZMax Abort=0
UNET Convert EG Bridges=0
UNET Use Existing IB Tables=0
UNET Froude Limit=0
UNET Froude Power=0
Write IC File=0
Echo Input=False
Echo Output=False
Write Detailed=0

--- COWCK.f01 (steady flow) ---

Flow Title=NFF Regression Equation
Program Version=4.00
Number of Profiles=1
Profile Names=P100yr
River Rch & RM=COWCK,Main      ,11620.1
913.1610
River Rch & RM=COWCK,Main      ,9120.1
989.6664
River Rch & RM=COWCK,Main      ,8755.1
1111.543
River Rch & RM=COWCK,Main      ,7693.3
1160.105
River Rch & RM=COWCK,Main      ,5397.2
1248.583
River Rch & RM=COWCK,Main      ,3120.1
1376.954
River Rch & RM=COWCK,Main      ,584.6
1496.184
River Rch & RM=COWCK,Main      ,254.1
1497.603
Boundary for River Rch & Prof#=COWCK,Main      ,1
Up Type=0
Dn Type=3
Dn Slope=0.018125

--- COWCK.g01 (geometry) ---

Geom Title=USGS 10m DEM
Program Version=4.10

River Reach=COWCK           ,Main
Reach XY= 30
     1770351.564      315764.283     1770342.814      316251.294
     1769984.342      316927.335     1769938.335      317489.748
     1769971.321        317792.7     1770037.293      318017.439
     1770289.897       318438.36     1770783.821       318869.35
     1771009.515      319016.485     1771285.557      319459.193
     1771440.939      319803.117     1771642.154      320080.252
     1771826.876      320410.738     1771837.293      321105.808
     1771794.932      321435.808      1771822.71      321671.155
     1771594.238      322495.807     1771659.515      322675.669
     1771801.182      322930.669     1771809.515      323125.252
     1771781.043      323298.169     1771808.821      323461.988
     1772093.543      324018.932     1772207.432      324117.544
     1772524.793      324289.766      1772860.73      324632.787
     1773021.147      324698.933     1773521.668      324693.724
     1773903.959      324808.308     1774235.731      324799.453

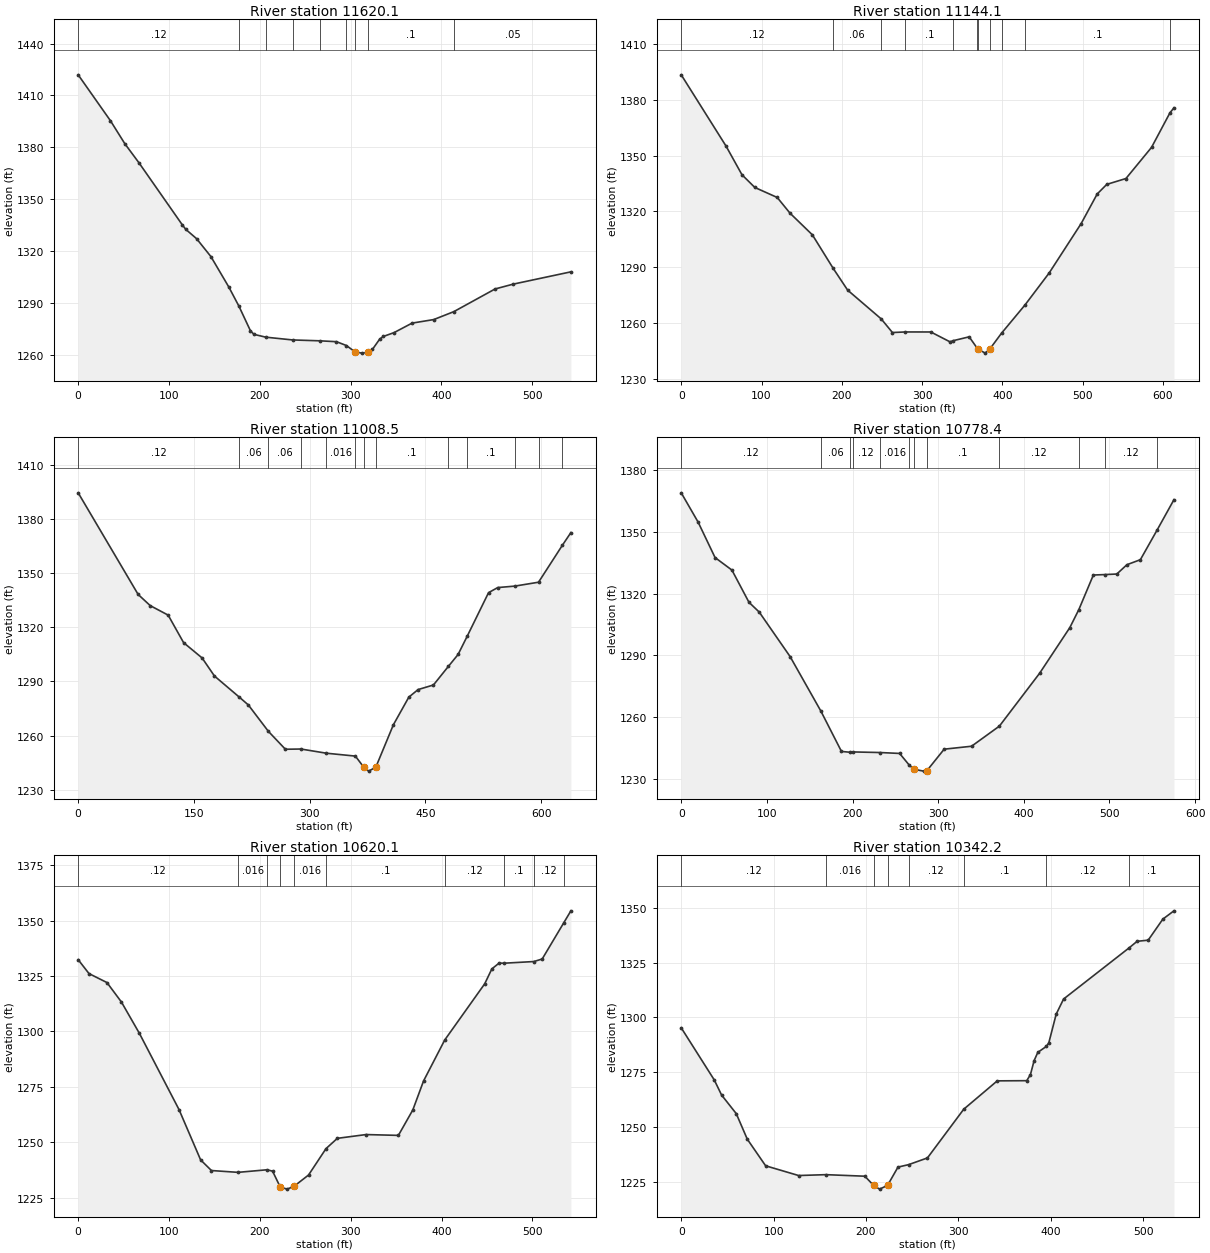
Type RM Length L Ch R = 1 ,11620.1 ,467.4,476,484.3
XS GIS Cut Line= 3
     1770040.358      315790.674     1770352.089      315774.269
      1770582.28      315762.155
#Sta/Elev= 30
       0 1421.91    35.6  1395.3    51.4 1382.03    67.2 1370.81   114.6 1335.14
   118.5 1332.47   130.4 1327.08   146.2  1316.7     166 1299.01  177.111287.936
   189.7  1273.8   193.6 1271.68  206.691270.052  236.261268.447  265.841267.954
   284.5 1267.44  295.421265.223   304.7 1261.64   312.2 1260.82   319.7 1261.31
   324.1 1262.98     332 1268.86     336 1270.45   347.9 1272.69   367.8  1278.2
   391.6 1280.24  413.731284.825   459.2 1297.96   479.1 1300.75   542.7 1307.87
#Mann= 9 ,-1 , 0
       0     .12       0  177.11     .06       0  206.69     .08       0
  236.26     .06       0  265.84    .016       0  295.42      .1       0
   304.7    .045       0   319.7      .1       0  413.73     .05       0
Bank Sta=304.7,319.7
XS Rating Curve= 0 ,0
Exp/Cntr=0.3,0.1

Type RM Length L Ch R = 1 ,11144.1 ,116.7,135.7,154.4
XS GIS Cut Line= 2
     1769971.746      316183.631      1770576.56      316288.367
#Sta/Elev= 30
       0  1393.3    55.8  1355.1    75.7 1339.68    91.7 1332.88   119.6 1327.51
   135.5  1319.1   163.4 1307.46   189.21289.558   207.3 1277.82  249.15 1262.37
   263.1 1255.07  279.131255.375   310.9 1255.37   334.8 1250.08  339.081250.725
   358.7 1252.76  369.061246.446   369.2 1246.36   378.6 1244.02   384.2  1246.1
  399.031254.717  427.951269.694   458.4 1287.04   498.2 1313.51   518.2 1329.39
   530.1 1334.53     554 1337.68   585.9 1354.39  608.871372.959   613.8 1375.58
#Mann= 11 ,-1 , 0
       0     .12       0   189.2     .06       0  249.15     .06       0
  279.13      .1       0  339.08    .016       0  369.06      .1       0
   369.2    .045       0   384.2      .1       0  399.03     .12       0
  427.95      .1       0  608.87     .12       0
Bank Sta=369.2,384.2
XS Rating Curve= 0 ,0
Exp/Cntr=0.3,0.1

Type RM Length L Ch R = 1 ,11008.5 ,233.9,230.1,225.2
XS GIS Cut Line= 4
      1769970.53        316190.6     1770085.576      316209.419
     1770371.626      316434.309     1770523.322      316478.691
#Sta/Elev= 30
       0 1394.44    77.7 1338.15    93.3 1331.97   116.6 1326.69   136.6 1311.45
   160.6 1302.96   176.6 1292.96  208.931281.214   220.5 1276.93   246.5  1262.3
   268.5 1252.39  288.591252.518  321.641250.197  359.221248.597  370.391242.281
   376.5 1240.27  385.751242.491   408.5 1265.98   428.5 1281.27   440.5 1285.45
   460.4    1288  479.731298.293   492.3 1304.88  504.251315.107   531.8 1339.14
   543.7 1341.96   565.81342.764  596.571344.921  627.351365.324   638.5 1372.42
#Mann= 13 ,-1 , 0
       0     .12       0  208.93     .06       0   246.5     .06       0
  288.59      .1       0  321.64    .016       0  359.22      .1       0
  370.39    .045       0  385.75      .1       0  479.73     .12       0
  504.25      .1       0   565.8     .12       0  596.57      .1       0
  627.35     .12       0
Bank Sta=370.39,385.75
XS Rating Curve= 0 ,0
Exp/Cntr=0.3,0.1

Type RM Length L Ch R = 1 ,10778.4 ,165.1,158.3,154.4
XS GIS Cut Line= 4
     1769921.975      316440.264     1769984.043      316451.808
     1770268.154      316623.197     1770443.128      316666.783
#Sta/Elev= 30
       0 1368.98    19.7 1354.76    39.5 1337.51    59.2 1331.42    79.1 1315.76
    91.1    1311   127.1 1289.39  163.031262.896   187.1 1243.26  197.52 1242.85
  199.981243.026  232.021242.732     255 1242.29  266.511236.469   271.9 1234.57
     283 1233.69   286.9 1233.93     307 1244.36     339 1245.79   371.51255.574
   418.5 1281.29   453.7 1303.44  464.251312.214   481.2 1329.02  494.691329.241
   508.6 1329.51   520.4 1334.04   536.1 1336.47  555.571350.837   575.3 1365.64
#Mann= 12 ,-1 , 0
       0     .12       0  163.03     .06       0  197.52     .08       0
  199.98     .12       0  232.02    .016       0  266.51      .1       0
   271.9    .045       0   286.9      .1       0   371.5     .12       0
  464.25      .1       0  494.69     .12       0  555.57      .1       0
Bank Sta=271.9,286.9
XS Rating Curve= 0 ,0
Exp/Cntr=0.3,0.1

Type RM Length L Ch R = 1 ,10620.1 ,287,277.9,266.7
XS GIS Cut Line= 3
     1769877.425      316611.241     1770089.916       316699.01
     1770372.326      316832.846
#Sta/Elev= 30
       0 1332.35    11.9 1326.08    31.7 1322.03    47.6 1313.27    67.4 1299.14
     111  1264.8   134.8 1242.11   146.7 1237.32  175.951236.501  207.911237.661
     214 1237.03   222.4 1229.92   229.9 1228.94   237.4 1230.15   253.6  1235.3
  272.781247.178   285.3 1251.83   316.9 1253.53   352.5 1253.16   368.4 1264.64
   380.2 1277.69  403.531296.159   447.5 1321.46   455.4 1328.19   463.3 1330.79
   468.91330.759  501.581331.503   510.8 1332.65  534.271348.782   542.4 1354.36
#Mann= 10 ,-1 , 0
       0     .12       0  175.95    .016       0  207.91      .1       0
   222.4    .045       0   237.4    .016       0  272.78      .1       0
  403.53     .12       0   468.9      .1       0  501.58     .12       0
  534.27      .1       0
Bank Sta=222.4,237.4
XS Rating Curve= 0 ,0
Exp/Cntr=0.3,0.1

Type RM Length L Ch R = 1 ,10342.2 ,224.8,222.1,220.4
XS GIS Cut Line= 3
     1769790.344      316864.634     1769884.745      316937.333
     1770294.901      316995.927
#Sta/Elev= 30
       0 1295.27    35.8 1271.45    43.7 1264.57    59.6 1256.08    71.5 1244.44
    91.4 1232.26   127.1 1227.82   156.71228.216   198.8 1227.51   208.4 1223.27
   214.8 1221.61   223.4 1223.32   234.7 1231.67  246.211232.792   266.6 1235.86
  305.89  1258.1   342.2 1271.05   374.1 1271.13   378.1 1273.88   382.1  1280.3
   386.1 1284.05  395.391286.801     398  1288.4     406 1301.52     414 1308.42
   484.91331.756   493.6 1334.77   505.6 1335.29   521.5 1344.91   533.5 1348.69
#Mann= 8 ,-1 , 0
       0     .12       0   156.7    .016       0   208.4    .045       0
   223.4    .016       0  246.21     .12       0  305.89      .1       0
  395.39     .12       0   484.9      .1       0
Bank Sta=208.4,223.4
XS Rating Curve= 0 ,0
Exp/Cntr=0.3,0.1

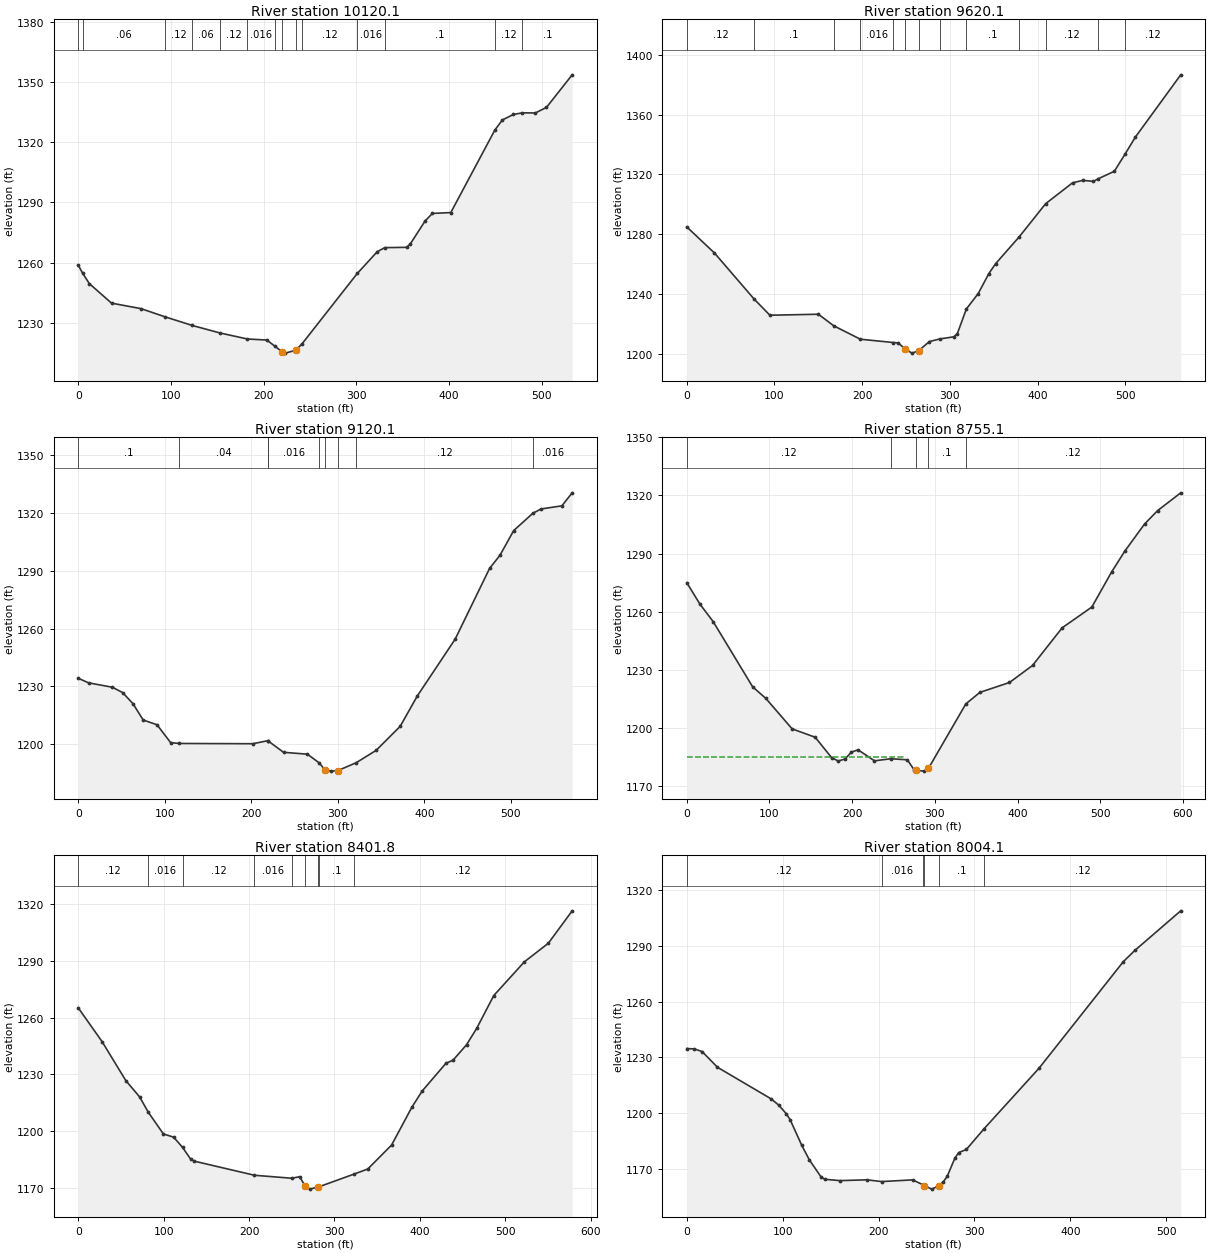
Type RM Length L Ch R = 1 ,10120.1 ,511,500,488.7
XS GIS Cut Line= 3
     1769740.069      317156.746     1769966.842      317172.292
     1770270.783      317202.228
#Sta/Elev= 30
       0 1258.83    4.661254.859      12 1249.61    35.9 1239.92    67.8 1237.17
   93.471233.135  123.081228.797  152.691225.105  182.29 1222.09   203.4 1221.56
   211.91218.561   219.8 1215.71   223.3 1215.05   234.8 1216.52  241.541219.778
   300.9 1254.67   322.5 1265.53  330.581267.534   354.2 1267.69   358.2 1269.41
   374.1 1280.82     382 1284.56   401.8 1284.98  449.291326.006   457.4 1331.05
   469.3 1333.79  478.971334.595     493 1334.54     505 1337.32   532.7 1353.51
#Mann= 14 ,-1 , 0
       0     .12       0    4.66     .06       0   93.47     .12       0
  123.08     .06       0  152.69     .12       0  182.29    .016       0
   211.9      .1       0   219.8    .045       0   234.8      .1       0
  241.54     .12       0   300.9    .016       0  330.58      .1       0
  449.29     .12       0  478.97      .1       0
Bank Sta=219.8,234.8
XS Rating Curve= 0 ,0
Exp/Cntr=0.3,0.1

Type RM Length L Ch R = 1 ,9620.1  ,511.1,500,487.5
XS GIS Cut Line= 3
     1769699.576      317727.594     1769949.706      317669.558
     1770250.271      317609.515
#Sta/Elev= 30
       0 1284.77    31.6 1267.28   76.69 1236.54    94.8 1225.64   150.1 1226.32
  167.651218.547  197.971209.593  235.281207.387     241 1207.12   249.3 1202.98
   256.8 1200.28   264.3 1201.84   276.7 1208.02  288.721209.797   304.5 1211.19
   308.5 1213.28  318.841229.828   332.4 1240.18   344.4 1253.46   352.3 1260.23
  379.081278.089   409.21300.285   439.9 1314.27   451.8 1315.95   463.8 1315.22
  469.441317.058   487.6    1322  499.551333.236   511.5 1344.81   563.3 1386.56
#Mann= 13 ,-1 , 0
       0     .12       0   76.69      .1       0  167.65     .06       0
  197.97    .016       0  235.28      .1       0   249.3    .045       0
   264.3      .1       0  288.72     .12       0  318.84      .1       0
  379.08    .016       0   409.2     .12       0  469.44      .1       0
  499.55     .12       0
Bank Sta=249.3,264.3
XS Rating Curve= 0 ,0
Exp/Cntr=0.3,0.1

Type RM Length L Ch R = 1 ,9120.1  ,371.9,365,358
XS GIS Cut Line= 3
      1769850.29      318285.836     1770103.925      318139.908
     1770345.126      318001.135
#Sta/Elev= 30
       0 1234.26    11.9 1231.88    39.5 1229.59    51.4  1226.8    63.3 1221.02
    75.1 1212.57      91 1210.13   106.8 1200.85  116.79  1200.4   201.7 1200.26
  219.021201.826  219.191201.802   237.3 1195.81   264.9 1194.84  278.421190.344
   285.1 1186.79   292.6 1186.04   300.1 1186.33  321.241190.391   344.3 1196.82
   372.1 1209.28     392 1225.13   435.7 1254.59   475.5 1291.34   487.4 1298.06
   503.3 1310.92  525.691319.992   535.1 1322.15     559 1323.77   570.9 1330.52
#Mann= 9 ,-1 , 0
       0      .1       0  116.79     .04       0  219.02      .1       0
  219.19    .016       0  278.42      .1       0   285.1    .045       0
   300.1      .1       0  321.24     .12       0  525.69    .016       0
Bank Sta=285.1,300.1
XS Rating Curve= 0 ,0
Exp/Cntr=0.3,0.1

Type RM Length L Ch R = 1 ,8755.1  ,357.8,353.3,348.6
XS GIS Cut Line= 2
     1770082.355      318632.251     1770536.258      318243.843
#Sta/Elev= 30
       0 1274.97    15.9 1263.92    31.9 1254.91    79.6  1221.3    95.6 1215.29
   127.4 1199.57   155.3 1195.25   175.2 1184.71   183.2 1182.99   191.2 1184.01
   199.1 1187.53   207.1 1188.79     227 1183.08  246.671184.159   266.8 1183.62
   274.8 1178.53   277.2 1178.15   286.8 1177.77   292.2 1179.13  337.53 1212.46
   354.5 1218.39   390.3 1223.49   418.2 1232.28     454 1251.69   489.9  1262.4
   513.8 1280.49   529.7 1291.19   553.6  1305.2   569.5 1312.16   597.4 1321.32
#Mann= 5 ,-1 , 0
       0     .12       0  246.67    .016       0   277.2    .045       0
   292.2      .1       0  337.53     .12       0
#XS Ineff= 2 , 0
          261.92 1185.24
Permanent Ineff=
       F       F
Bank Sta=277.2,292.2
XS Rating Curve= 0 ,0
Exp/Cntr=0.3,0.1

Type RM Length L Ch R = 1 ,8401.8  ,396.8,397.7,398.4
XS GIS Cut Line= 2
     1770373.348      318886.783     1770764.021      318460.446
#Sta/Elev= 30
       0 1265.14    27.9 1247.32    55.8 1226.67    71.8 1218.15   82.031210.008
    99.7 1198.54   111.7 1196.85   122.11191.474   131.6 1185.26   135.6  1184.2
  206.321176.724  250.041175.143   259.2 1175.96   265.7 1171.02   271.2  1169.4
   280.7 1170.54  282.351170.718  322.411177.256     339 1180.03   366.9  1192.7
   390.8 1212.81   402.8 1221.28   430.7 1235.95   438.7 1237.43   454.6 1245.64
   466.6 1254.36   486.5 1271.64   522.4 1289.47   550.4 1299.26   578.3 1316.38
#Mann= 9 ,-1 , 0
       0     .12       0   82.03    .016       0   122.1     .12       0
  206.32    .016       0  250.04     .12       0   265.7    .045       0
   280.7     .12       0  282.35      .1       0  322.41     .12       0
Bank Sta=265.7,280.7
XS Rating Curve= 0 ,0
Exp/Cntr=0.3,0.1

Type RM Length L Ch R = 1 ,8004.1  ,305.3,310.8,316.5
XS GIS Cut Line= 2
     1770698.001      319110.741     1771051.995      318736.384
#Sta/Elev= 30
       0 1234.79       8 1234.58      16 1233.17      32 1224.72    87.9 1207.74
    95.9 1204.34   103.8  1199.7   107.8  1196.5   119.8 1182.85   127.8 1174.92
   139.8 1165.88   143.8 1164.43   159.8 1163.71   187.7 1164.14  203.251163.197
   235.6 1164.11  246.241161.505   247.8 1160.99   255.6 1159.13   262.8 1160.89
   267.6  1163.1   271.6 1165.96   279.6 1175.75   283.6  1178.8   291.6 1180.47
   310.21191.696   367.4 1224.19   455.3 1281.54   467.3 1287.58   515.2 1308.92
#Mann= 6 ,-1 , 0
       0     .12       0  203.25    .016       0  246.24      .1       0
   247.8    .045       0   262.8      .1       0   310.2     .12       0
Bank Sta=247.8,262.8
XS Rating Curve= 0 ,0
Exp/Cntr=0.3,0.1

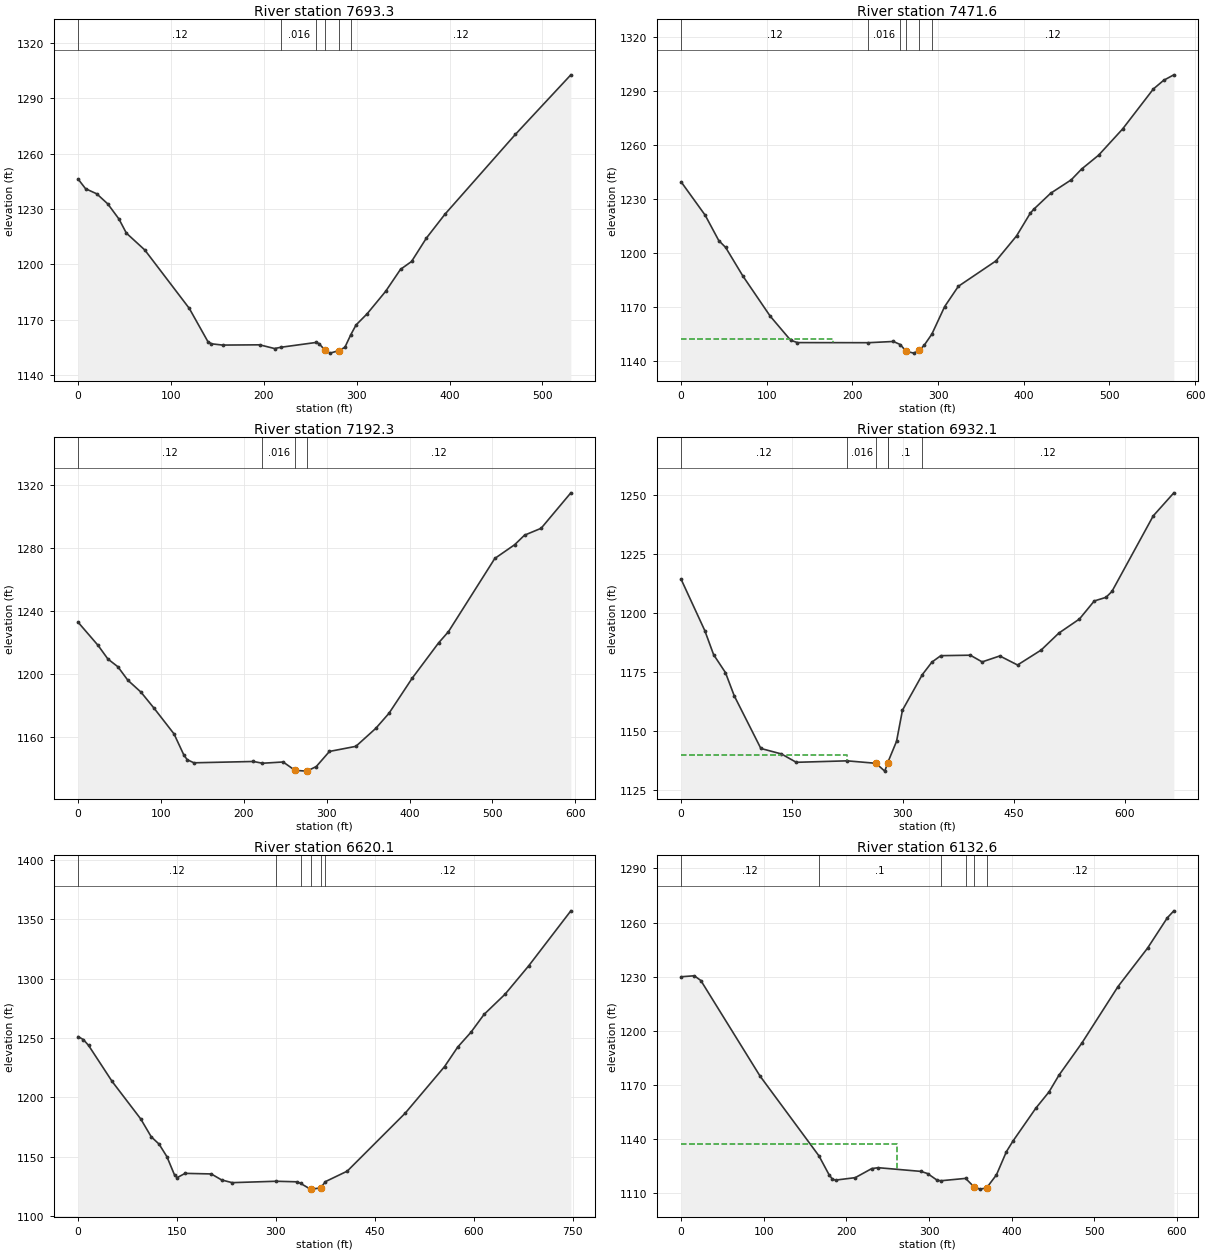
Type RM Length L Ch R = 1 ,7693.3  ,220.9,221.7,222
XS GIS Cut Line= 2
     1770871.612      319306.921     1771290.703       318981.32
#Sta/Elev= 30
       0 1246.15       8 1240.97      20 1238.22    31.9 1232.75    43.9 1224.58
    51.9 1216.93    71.8 1207.76   119.7 1176.11   139.7 1158.15   143.6 1156.93
   155.6 1156.24   195.5 1156.38   211.5 1154.38  218.82 1155.09  256.231157.662
   259.4 1157.06   265.8 1153.51   271.3 1151.88   280.8 1153.24   287.3 1155.03
  293.631161.838   299.3 1167.13   311.2 1173.17   331.2 1185.37   347.2 1197.28
   359.1 1201.54   375.1 1214.23     395 1227.11   470.9 1270.39   530.7  1302.7
#Mann= 6 ,-1 , 0
       0     .12       0  218.82    .016       0  256.23      .1       0
   265.8    .045       0   280.8      .1       0  293.63     .12       0
Bank Sta=265.8,280.8
XS Rating Curve= 0 ,0
Exp/Cntr=0.3,0.1

Type RM Length L Ch R = 1 ,7471.6  ,277,279.3,281.5
XS GIS Cut Line= 2
     1770988.014      319488.398     1771447.168      319141.866
#Sta/Elev= 30
       0 1239.59      28 1221.13    43.9 1207.04    51.9 1203.24    71.9 1187.47
   103.9 1165.11   127.8 1151.71   135.8 1150.42  218.691150.361   247.7 1151.04
  255.691149.353   262.7 1145.58   271.6 1144.57   277.7 1146.03   283.6 1148.86
  292.691155.142   307.6  1170.4   323.6 1181.66   367.5 1195.75   391.5  1209.6
   407.5 1222.18   411.5 1224.37   431.4 1233.32   455.4 1240.76   467.4  1246.7
   487.4 1254.46   515.3 1268.95   551.3  1291.2   563.3    1296   575.2 1299.04
#Mann= 6 ,-1 , 0
       0     .12       0  218.69    .016       0  255.69      .1       0
   262.7    .045       0   277.7      .1       0  292.69     .12       0
#XS Ineff= 2 , 0
          177.09 1152.16
Permanent Ineff=
       F       F
Bank Sta=262.7,277.7
XS Rating Curve= 0 ,0
Exp/Cntr=0.3,0.1

Type RM Length L Ch R = 1 ,7192.3  ,257.6,260.3,262.7
XS GIS Cut Line= 2
     1771111.496      319717.607     1771606.287      319387.746
#Sta/Elev= 30
       0 1232.82      24 1218.15    35.9 1209.46    47.9 1204.56    59.9 1196.01
    75.8 1188.39    91.8 1178.04   115.7 1161.82   127.7 1148.23   131.7 1145.38
   139.7 1143.43   211.5 1144.27  222.471143.149   247.4 1143.95   261.7 1138.64
   275.4 1138.13   276.7 1138.32   287.4 1141.04   303.3 1150.66   335.2  1153.9
   359.2 1165.33   375.2 1174.95   403.1  1197.2     435  1219.7     447 1226.91
   502.9 1273.46   526.8 1282.18   538.8 1288.28   558.8 1292.65   594.7 1315.22
#Mann= 4 ,-1 , 0
       0     .12       0  222.47    .016       0   261.7    .045       0
   276.7     .12       0
Bank Sta=261.7,276.7
XS Rating Curve= 0 ,0
Exp/Cntr=0.3,0.1

Type RM Length L Ch R = 1 ,6932.1  ,317.3,312,306.3
XS GIS Cut Line= 2
     1771203.344      319938.792     1771783.932      319611.191
#Sta/Elev= 30
       0 1214.41    31.9 1192.75    43.9  1182.5    59.9 1174.92    71.8 1165.08
   107.8 1142.77   135.7 1140.43   155.7  1136.9  224.521137.522   263.5 1136.48
   275.4 1133.16   279.4 1136.54   280.51137.542   291.4 1145.81   299.4 1158.99
  326.261174.049   339.3 1179.38   351.3 1182.09   391.2 1182.29   407.2 1179.45
   431.1 1181.97   455.1 1178.14     487 1184.46     511 1191.66   538.9 1197.64
   558.9 1205.27   574.8 1206.81   582.8  1209.3   638.7 1241.33   666.6  1251.1
#Mann= 6 ,-1 , 0
       0     .12       0  224.52    .016       0   263.5    .045       0
   279.4    .016       0   280.5      .1       0  326.26     .12       0
#XS Ineff= 2 , 0
          223.94  1140.1
Permanent Ineff=
       F       F
Bank Sta=263.5,279.4
XS Rating Curve= 0 ,0
Exp/Cntr=0.3,0.1

Type RM Length L Ch R = 1 ,6620.1  ,460.5,487.5,515
XS GIS Cut Line= 3
     1771338.131      320276.502     1771623.575      320056.718
     1771927.527      319816.759
#Sta/Elev= 30
       0 1251.09     7.9 1248.61    15.8 1243.68    51.5 1213.36      95 1181.68
   110.8 1166.74   122.7 1160.56   134.6 1149.98   146.5 1134.12   150.4 1132.37
   162.3 1135.89   201.9  1135.4   217.7 1130.33   233.6 1128.06  300.351129.233
   332.5 1128.76  337.631127.376   352.3  1122.6   352.8 1122.61   367.8 1123.57
  375.041128.903   408.2 1137.75     496  1186.5   555.9 1225.88   575.8 1242.29
   595.8 1254.71   615.8 1269.82   647.7 1286.87   683.6 1310.82   747.5 1357.12
#Mann= 6 ,-1 , 0
       0     .12       0  300.35    .016       0  337.63      .1       0
   352.8    .045       0   367.8      .1       0  375.04     .12       0
Bank Sta=352.8,367.8
XS Rating Curve= 0 ,0
Exp/Cntr=0.3,0.1

Type RM Length L Ch R = 1 ,6132.6  ,213.9,212.7,211.3
XS GIS Cut Line= 2
     1771468.675      320467.381     1772064.161      320498.631
#Sta/Elev= 30
       0  1229.9    15.9 1230.45    23.8 1227.81    95.4 1174.84  166.761130.524
   178.9 1120.14   182.9  1117.7   186.8 1117.08   210.7 1118.45   230.6 1123.47
   238.5 1123.97   290.2 1121.92   298.2 1120.72   310.1 1116.93  314.641116.741
  344.221118.034   354.7 1113.23   361.8 1112.08   369.7 1112.78   381.6 1120.03
   393.6 1132.84   401.5  1138.7   429.3 1157.03   445.2 1166.02   457.2 1175.28
     485 1193.15   528.7 1224.46   564.5 1245.81   588.4 1262.62   596.3 1266.48
#Mann= 6 ,-1 , 0
       0     .12       0  166.76      .1       0  314.64    .016       0
  344.22     .12       0   354.7    .045       0   369.7     .12       0
#XS Ineff= 2 , 0
           260.8 1136.92
Permanent Ineff=
       F       F
Bank Sta=354.7,369.7
XS Rating Curve= 0 ,0
Exp/Cntr=0.3,0.1

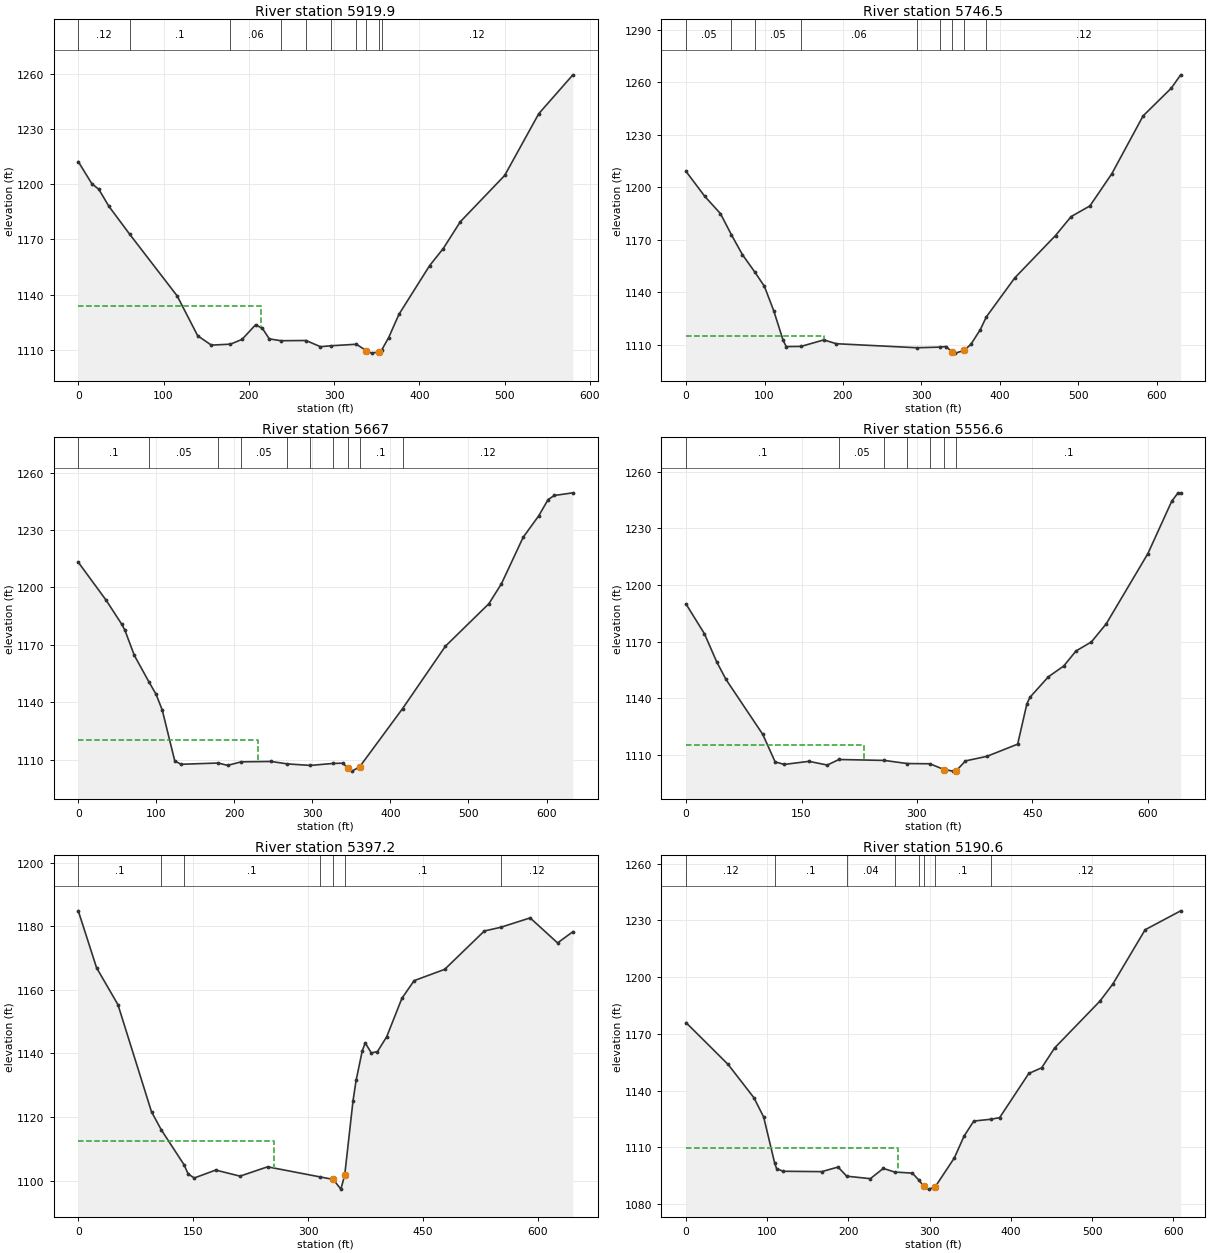
Type RM Length L Ch R = 1 ,5919.9  ,174.4,173.4,172.4
XS GIS Cut Line= 2
     1771486.369      320691.644      1772066.23       320702.06
#Sta/Elev= 30
       0 1212.24      16 1200.18      24 1197.26      36 1187.93   60.251172.832
     116 1139.29     140  1117.7     156 1112.59  178.41 1113.11     192 1115.69
     208 1123.67     216 1121.63     224 1115.99  237.491114.983  267.031115.093
     284 1111.74  296.57 1112.24  326.121113.068   337.8 1109.57     344 1108.24
   352.8 1109.01  355.661109.832     364  1116.7     376  1129.3     412 1155.78
     428 1165.06     448  1179.6     500 1204.73     540 1238.29     580 1259.38
#Mann= 10 ,-1 , 0
       0     .12       0   60.25      .1       0  178.41     .06       0
  237.49      .1       0  267.03     .06       0  296.57    .016       0
  326.12      .1       0   337.8    .045       0   352.8      .1       0
  355.66     .12       0
#XS Ineff= 2 , 0
          213.92 1133.63
Permanent Ineff=
       F       F
Bank Sta=337.8,352.8
XS Rating Curve= 0 ,0
Exp/Cntr=0.3,0.1

Type RM Length L Ch R = 1 ,5746.5  ,79.4,79.5,79.7
XS GIS Cut Line= 2
     1771488.727      320873.545     1772119.308      320868.164
#Sta/Elev= 30
       0 1208.98      24 1194.67    43.9 1184.84   57.891172.695    71.8 1161.44
   87.43 1151.58    99.8 1143.35   111.8 1129.29   123.7 1112.43   127.7 1108.81
   146.51108.906   175.6 1112.63   191.6 1110.45  294.191108.149  323.721108.502
   331.3 1108.85   339.4 1105.72   343.2 1105.07   354.4 1106.59   363.2 1110.13
   375.2 1118.58   382.81125.786   419.1 1148.12     471 1172.33   490.9 1183.16
   514.9 1189.28   542.8 1207.68   582.7 1240.77   618.6 1256.61   630.6 1264.24
#Mann= 9 ,-1 , 0
       0     .05       0   57.89      .1       0   87.43     .05       0
   146.5     .06       0  294.19    .016       0  323.72      .1       0
   339.4    .045       0   354.4      .1       0   382.8     .12       0
#XS Ineff= 2 , 0
          176.26 1114.59
Permanent Ineff=
       F       F
Bank Sta=339.4,354.4
XS Rating Curve= 0 ,0
Exp/Cntr=0.3,0.1

Type RM Length L Ch R = 1 ,5667    ,110.1,110.3,110.6
XS GIS Cut Line= 2
     1771485.472       320951.67     1772119.308      320948.734
#Sta/Elev= 30
       0 1213.14    35.9 1193.17    55.8 1180.65    59.8 1177.56    71.8 1164.48
   90.68 1150.48    99.7 1144.09   107.6 1135.89   123.6 1109.36   131.6 1107.52
  179.291108.175   191.4 1106.95  208.831108.803   247.2 1108.99   267.91107.716
  297.44 1106.92  326.981107.981   338.8 1108.09   345.6 1105.52   350.8 1103.94
   360.6 1106.22  415.581136.645   470.4 1169.22   526.2 1191.48   542.2 1201.86
   570.1  1226.2     590 1237.39     602 1245.85   609.9 1248.02   633.8 1249.41
#Mann= 10 ,-1 , 0
       0      .1       0   90.68     .05       0  179.29      .1       0
  208.83     .05       0   267.9     .06       0  297.44    .016       0
  326.98      .1       0   345.6    .045       0   360.6      .1       0
  415.58     .12       0
#XS Ineff= 2 , 0
          230.68 1120.18
Permanent Ineff=
       F       F
Bank Sta=345.6,360.6
XS Rating Curve= 0 ,0
Exp/Cntr=0.3,0.1

Type RM Length L Ch R = 1 ,5556.6  ,159.1,159.4,159.2
XS GIS Cut Line= 3
     1771495.672      321059.656     1772022.234      321060.697
     1772122.234      321001.843
#Sta/Elev= 30
       0 1189.85    23.9  1174.1    39.9 1159.16    51.9 1149.91    99.7 1120.78
   115.7 1106.25   127.6 1104.89   159.6 1106.53   183.5 1104.56  198.631107.504
  257.711107.008  287.241105.361  316.781105.238   335.1 1102.19     347 1101.34
     351 1101.54     363 1106.76   390.9 1109.18   430.8 1115.64   442.8 1137.03
   446.8 1140.48   470.7 1151.32   490.7 1157.05   506.6    1165   526.6 1169.79
   545.9  1179.4     600  1216.6     631 1244.37   638.7 1248.52   642.6 1248.78
#Mann= 7 ,-1 , 0
       0      .1       0  198.63     .05       0  257.71     .06       0
  287.24    .016       0  316.78      .1       0   335.1    .045       0
     351      .1       0
#XS Ineff= 2 , 0
          231.68 1115.29
Permanent Ineff=
       F       F
Bank Sta=335.1,351
XS Rating Curve= 0 ,0
Exp/Cntr=0.3,0.1

Type RM Length L Ch R = 1 ,5397.2  ,206.2,206.6,206.8
XS GIS Cut Line= 2
     1771467.793      321211.983     1772113.452       321215.45
#Sta/Elev= 30
       0 1184.82    23.9 1166.92    51.8 1155.34    95.6 1121.68  108.381116.004
  137.911105.106   143.5 1102.14   151.4 1100.88   179.4 1103.37   211.2 1101.46
   247.1 1104.39  315.13 1101.24   332.8 1100.43   342.8 1097.38   347.8 1101.77
   358.7 1125.17   362.7 1131.56   370.7  1140.8   374.6 1143.32   382.6 1140.16
   390.6 1140.61   402.6 1145.24   422.5 1157.34   438.4 1162.88   478.3 1166.43
   530.1 1178.49  551.431179.642   589.9  1182.6   625.7 1174.74   645.7 1178.26
#Mann= 7 ,-1 , 0
       0      .1       0  108.38     .12       0  137.91      .1       0
  315.13    .016       0   332.8    .045       0   347.8      .1       0
  551.43     .12       0
#XS Ineff= 2 , 0
          255.54 1112.56
Permanent Ineff=
       F       F
Bank Sta=332.8,347.8
XS Rating Curve= 0 ,0
Exp/Cntr=0.3,0.1

Type RM Length L Ch R = 1 ,5190.6  ,202.2,200.5,198.7
XS GIS Cut Line= 2
     1771496.477      321415.646     1772105.638      321424.178
#Sta/Elev= 30
       0 1175.97    51.8 1153.87    83.6 1136.26    95.6 1126.04  109.251101.526
   111.5 1098.86   119.4  1097.4   167.2 1097.21   187.2 1099.64  197.861094.804
     227 1093.49   242.9 1098.91  256.941096.999   278.7 1096.42  286.481092.853
  293.041089.367   298.6 1087.96   306.5 1088.96   330.5 1104.51   342.4    1116
   354.4 1123.95   375.11124.882   386.2 1125.74   422.1 1149.09     438 1152.11
   453.9 1162.57   509.7 1187.32   525.6 1196.35   565.4 1225.07   609.2 1235.07
#Mann= 8 ,-1 , 0
       0     .12       0  109.25      .1       0  197.86     .04       0
  256.94    .016       0  286.48      .1       0  293.04    .045       0
   306.5      .1       0   375.1     .12       0
#XS Ineff= 2 , 0
          261.51 1109.96
Permanent Ineff=
       F       F
Bank Sta=293.04,306.5
XS Rating Curve= 0 ,0
Exp/Cntr=0.3,0.1

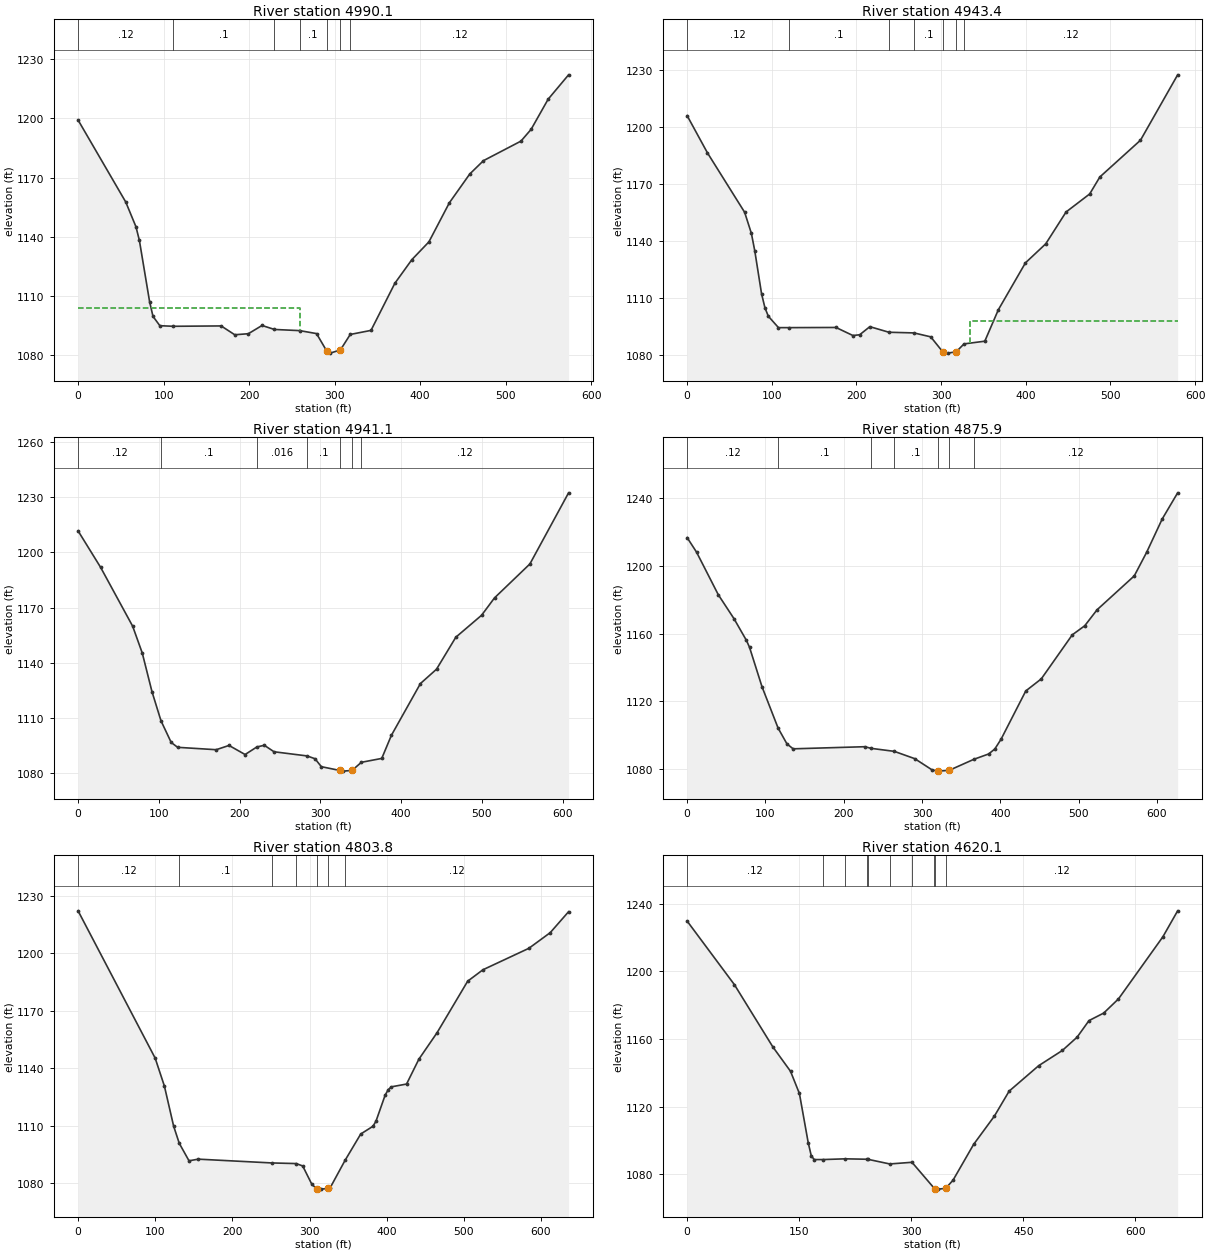
Type RM Length L Ch R = 1 ,4990.1  ,43.5,46.7,50
XS GIS Cut Line= 2
     1771523.923      321625.958     1772097.165      321608.155
#Sta/Elev= 30
       0 1199.09    55.8 1157.57    67.7 1145.08    71.7 1138.17    83.6 1107.27
    87.6 1099.76    95.6 1095.05  111.391094.745   167.3 1094.93   183.2 1090.46
   199.1 1090.99   215.1 1095.16  229.591093.144  259.141092.555   278.8 1091.06
   290.7 1082.25   294.7 1081.17   306.7 1082.76  318.24 1090.62   342.5 1092.67
   370.4 1116.51   390.3 1128.47   410.2 1137.45   434.1 1157.21     458 1171.81
     474 1178.54   517.8 1188.42   529.7 1194.38   549.6 1209.62   573.5 1221.96
#Mann= 7 ,-1 , 0
       0     .12       0  111.39      .1       0  229.59    .016       0
  259.14      .1       0   290.7    .045       0   306.7      .1       0
  318.24     .12       0
#XS Ineff= 2 , 0
          259.94 1104.05
Permanent Ineff=
       F       F
Bank Sta=290.7,306.7
XS Rating Curve= 0 ,0
Exp/Cntr=0.3,0.1

Type RM Length L Ch R = 1 ,4943.4  ,32.3,2.2,3.1
XS GIS Cut Line= 2
     1771515.429      321645.886     1772093.931      321678.386
#Sta/Elev= 30
       0 1206.14      24 1186.51    67.9 1155.21    75.9 1144.06    79.9 1134.83
    87.9 1112.25    91.9 1104.83    95.9 1100.38   107.9 1094.37  120.021094.373
   175.8 1094.46   195.8 1090.22   203.8 1090.61   215.8 1094.88  238.351091.939
  267.941091.583   287.7 1089.52  302.021081.584   307.7 1080.93  317.731081.622
   327.11085.797   351.6 1087.22   367.6  1103.8   399.6 1128.52   423.6 1138.57
   447.6 1155.35   475.5 1164.86   487.5 1173.81   535.5 1193.19   579.4 1227.67
#Mann= 7 ,-1 , 0
       0     .12       0  120.02      .1       0  238.35    .016       0
  267.94      .1       0  302.02    .045       0  317.73      .1       0
   327.1     .12       0
#XS Ineff= 2 , 0
                          334.09         1097.73
Permanent Ineff=
       F       F
Bank Sta=302.02,317.73
XS Rating Curve= 0 ,0
Exp/Cntr=0.3,0.1

Type RM Length L Ch R = 1 ,4941.1  ,59,65.2,50.3
XS GIS Cut Line= 4
     1771503.539      321674.654      1771768.73      321700.262
     1771819.511      321665.105     1772097.723      321687.241
#Sta/Elev= 30
       0 1211.75    27.8 1191.98    67.6 1159.85    79.5 1145.23    91.5 1124.26
  102.661108.382   115.3 1096.58   123.3 1093.93     171 1092.63   186.9 1094.95
   206.8 1090.01  221.361094.125   230.6 1095.04   242.6 1091.51  283.711089.235
   293.4  1087.7   301.2 1083.39   324.2 1081.32   328.2 1080.97   339.2 1081.35
  350.761085.771     376 1087.89     388 1100.52   423.9 1128.65   443.8 1136.45
   467.7 1153.86   499.6 1165.82   515.6 1175.27   559.4 1193.74   607.3 1232.46
#Mann= 7 ,-1 , 0
       0     .12       0  102.66      .1       0  221.36    .016       0
  283.71      .1       0   324.2    .045       0   339.2      .1       0
  350.76     .12       0
Bank Sta=324.2,339.2
XS Rating Curve= 0 ,0
Exp/Cntr=0.3,0.1

Type RM Length L Ch R = 1 ,4875.9  ,36.7,72.1,97.7
XS GIS Cut Line= 6
     1771490.084      321723.265     1771787.393      321752.345
     1771809.962      321729.341     1771820.813      321730.643
     1771844.684      321717.189     1772101.231      321737.588
#Sta/Elev= 30
       0 1216.76      12 1208.18    39.8 1182.99    59.8 1168.88    75.7 1156.04
    79.7 1151.92    95.6 1128.66   116.21104.185   127.5 1094.85   135.4 1091.93
     227 1093.18  234.911092.219  264.581090.439   290.8 1086.11     313 1079.44
   320.2 1078.75   334.6 1079.19  366.221085.724   385.1 1088.88     393 1091.81
     401  1097.6   432.6 1126.14   452.4 1133.27     492  1159.3   507.9 1164.65
   523.7 1174.12   571.2 1194.14     587 1208.08   606.8  1227.7   626.6 1243.22
#Mann= 7 ,-1 , 0
       0     .12       0   116.2      .1       0  234.91    .016       0
  264.58      .1       0   320.2    .045       0   334.6      .1       0
  366.22     .12       0
Bank Sta=320.2,334.6
XS Rating Curve= 0 ,0
Exp/Cntr=0.3,0.1

Type RM Length L Ch R = 1 ,4803.8  ,192.5,183.7,176.4
XS GIS Cut Line= 3
     1771475.395      321739.812     1771705.698      321765.689
     1772083.294      321909.347
#Sta/Elev= 30
       0 1222.04    99.9 1145.27   111.9 1130.67   123.9 1109.73  131.161100.831
   143.8  1091.7   155.8 1092.56   251.21090.582   282.81090.255   291.2    1089
     303 1079.46   309.1 1077.16   314.9 1076.93   324.1 1077.29   326.8 1077.66
  346.011091.887   366.4 1105.67   382.3 1109.72   386.2  1112.4   398.1 1126.01
   402.1 1128.79     406 1130.26   425.8 1131.72   441.7 1144.64   465.4 1158.53
     505 1185.35   524.8 1191.31   584.3 1202.49     612 1210.65   635.8 1221.58
#Mann= 7 ,-1 , 0
       0     .12       0  131.16      .1       0   251.2    .016       0
   282.8      .1       0   309.1    .045       0   324.1      .1       0
  346.01     .12       0
Bank Sta=309.1,324.1
XS Rating Curve= 0 ,0
Exp/Cntr=0.3,0.1

Type RM Length L Ch R = 1 ,4620.1  ,248.4,246.7,243.1
XS GIS Cut Line= 3
     1771395.725       321926.73     1771729.161      321968.935
      1772044.92      322024.357
#Sta/Elev= 30
       0 1229.79    63.3 1192.14   114.7 1155.32   138.4 1140.86   150.3 1127.72
   162.1 1098.58   166.1 1090.99     170  1088.6  181.921088.602  211.691089.039
  241.461088.783   241.71088.786  271.231086.004  301.011086.986  330.781071.612
   332.1 1071.25   336.1  1071.1  346.021071.548   355.9 1076.33   383.6 1097.62
   411.3  1114.3   431.1 1129.11   470.7  1144.2   502.3 1153.18   522.1 1161.06
     538 1170.87   557.7 1175.33   577.5 1183.73   636.9 1220.47   656.7 1235.86
#Mann= 10 ,-1 , 0
       0     .12       0  181.92     .06       0  211.69     .12       0
  241.46      .1       0   241.7     .12       0  271.23    .016       0
  301.01      .1       0  330.78     .12       0   332.1    .045       0
  346.02     .12       0
Bank Sta=332.1,346.02
XS Rating Curve= 0 ,0
Exp/Cntr=0.3,0.1