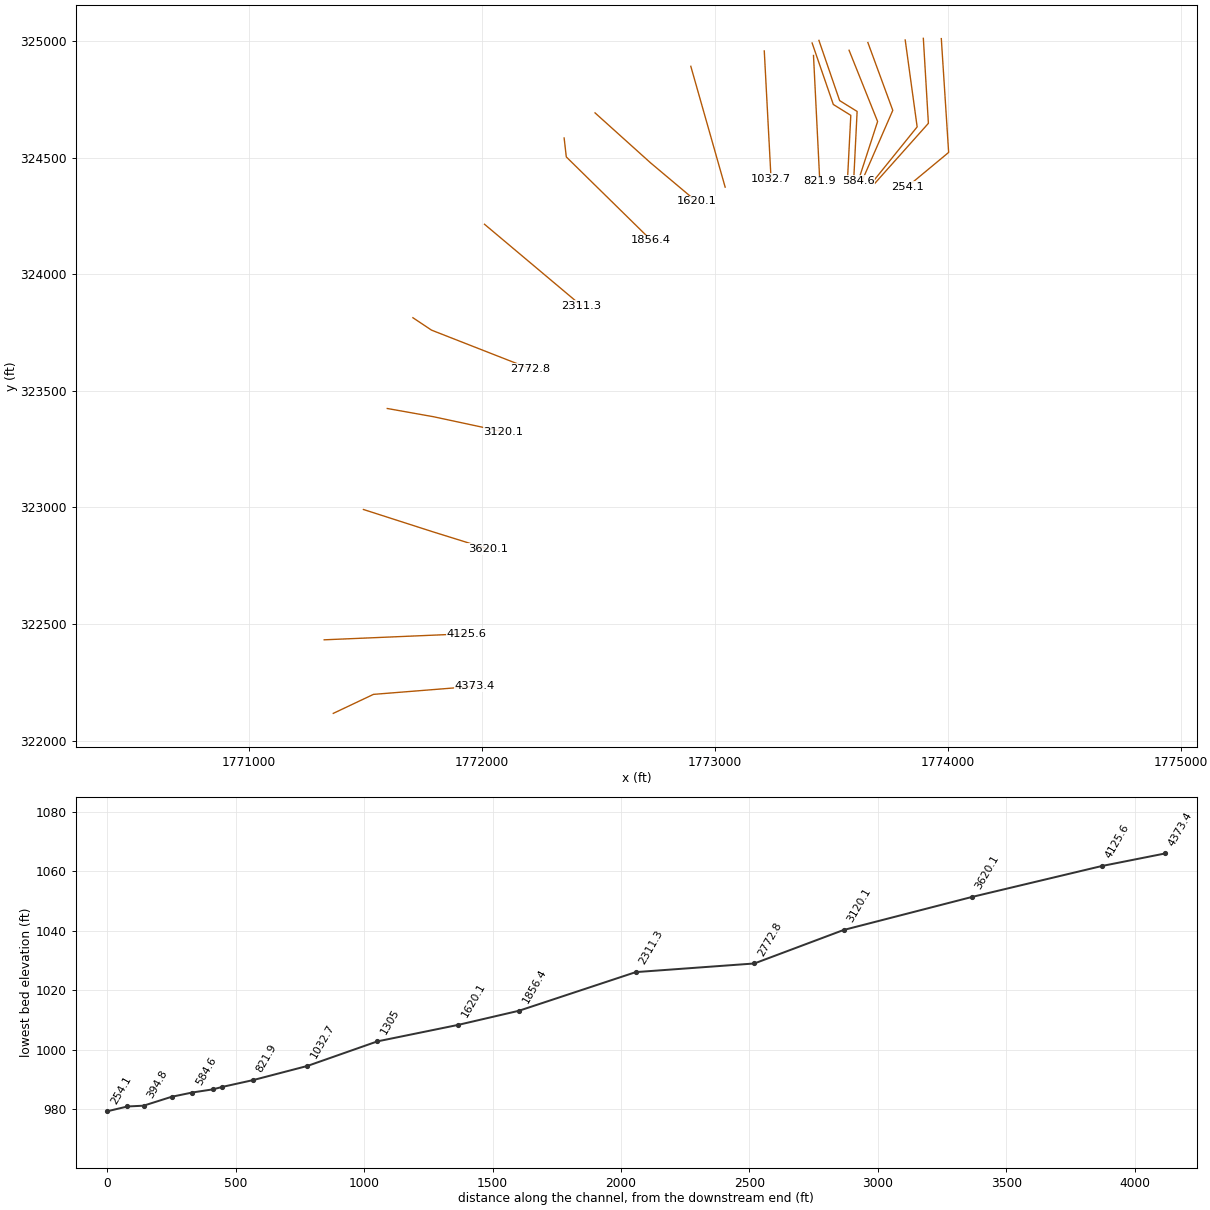
HEC-RAS study COWCK.prj: COWCK

--- COWCK.g01 (geometry) --- (continued)

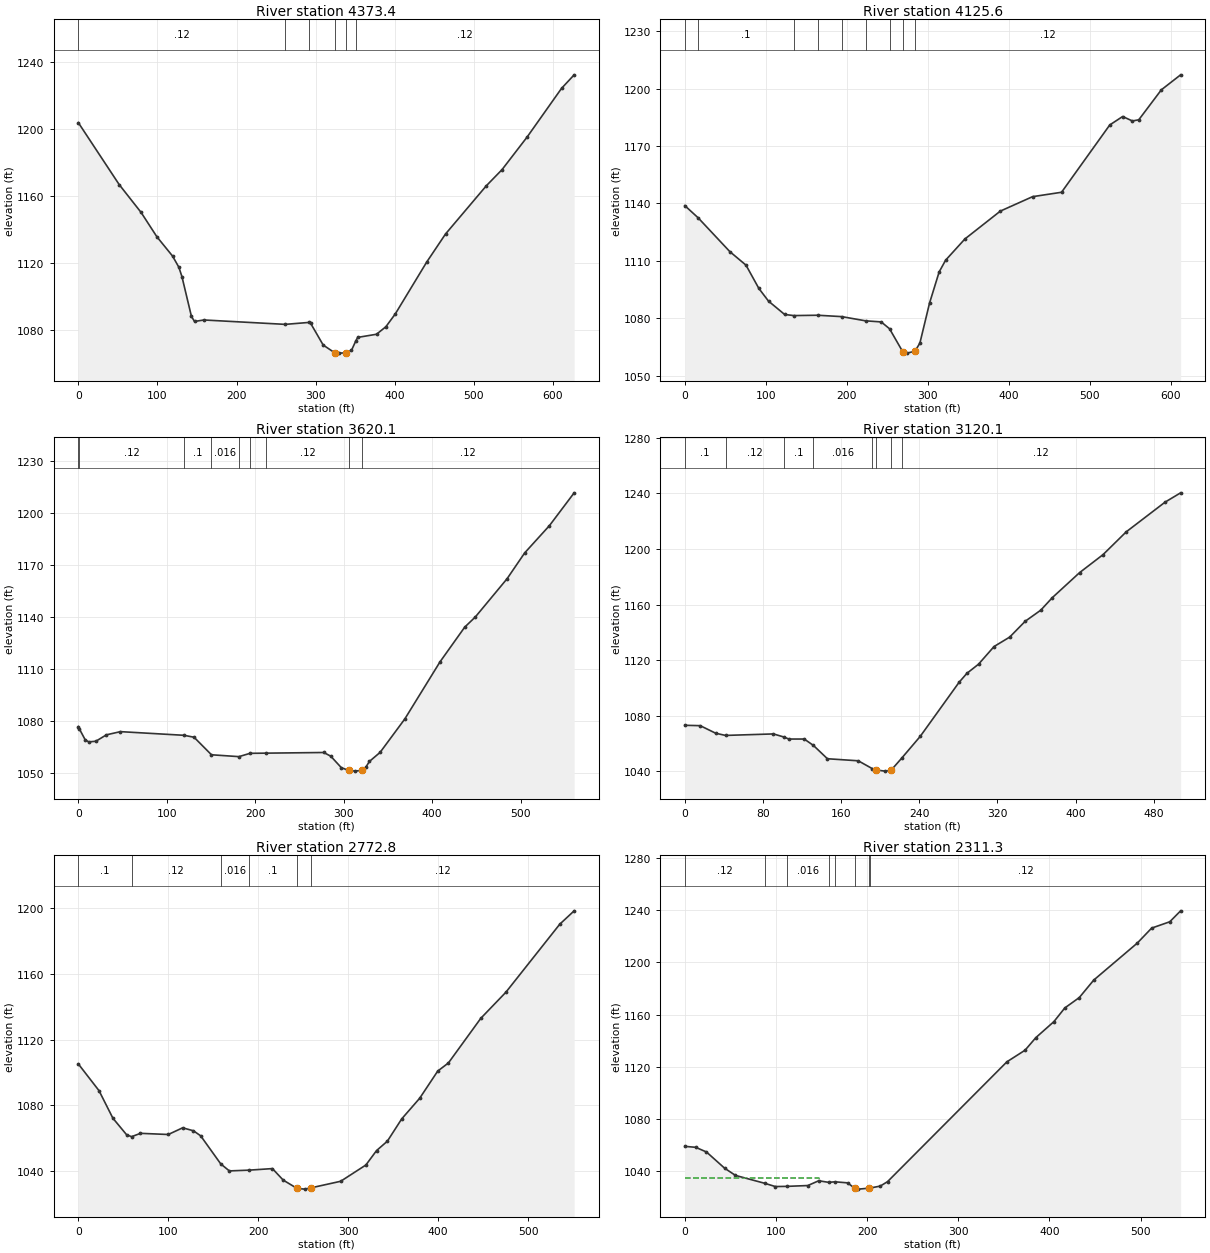
Type RM Length L Ch R = 1 ,4373.4  ,249.1,247.8,246.1
XS GIS Cut Line= 3
     1771362.651      322116.556     1771534.937      322198.067
     1771969.858      322232.861
#Sta/Elev= 30
       0 1203.72    51.6 1166.75    79.4 1150.04    99.3 1135.53   119.1 1124.02
   127.1 1117.32     131  1111.7     143 1087.94   146.9 1084.92   158.8  1085.8
  261.641083.179  291.271084.325   293.7 1083.82   309.6 1070.81     324 1066.25
   329.4 1065.99     339 1066.16   345.3 1067.59  350.531072.967   353.2 1075.39
     377 1077.27   388.9 1081.78   400.8 1089.46   440.5 1120.43   464.3 1137.21
   515.8 1165.97   535.7 1175.64   567.4 1195.11     611 1224.24   626.9  1232.3
#Mann= 6 ,-1 , 0
       0     .12       0  261.64    .016       0  291.27      .1       0
     324    .045       0     339      .1       0  350.53     .12       0
Bank Sta=324,339
XS Rating Curve= 0 ,0
Exp/Cntr=0.3,0.1

Type RM Length L Ch R = 1 ,4125.6  ,518.5,505.5,492.8
XS GIS Cut Line= 2
     1771323.547      322432.125     1771935.526      322458.167
#Sta/Elev= 30
       0 1138.84    16.41132.497    55.7 1114.77    75.6 1107.72    91.5 1095.55
   103.4 1088.93   123.3 1081.96  134.66 1081.37  164.221081.549  193.78 1080.83
  223.351078.627   242.6 1078.06  252.911074.497  269.061062.595   274.4 1061.75
   284.31062.731   290.4 1066.97   302.3 1087.84   314.2 1104.18   322.2 1110.32
     346  1121.4   389.8 1135.97   429.6 1143.51   465.4 1145.81     525    1181
   540.9  1185.4   552.9 1183.07   560.8 1183.68   588.7 1199.35   612.5 1207.18
#Mann= 9 ,-1 , 0
       0     .12       0    16.4      .1       0  134.66     .06       0
  164.22      .1       0  193.78     .12       0  223.35    .016       0
  252.91      .1       0  269.06    .045       0   284.3     .12       0
Bank Sta=269.06,284.3
XS Rating Curve= 0 ,0
Exp/Cntr=0.3,0.1

Type RM Length L Ch R = 1 ,3620.1  ,494.8,500,503.4
XS GIS Cut Line= 3
     1771492.032      322991.175     1771790.178      322895.342
      1772026.31      322821.792
#Sta/Elev= 30
       0    1077    1.041075.807     7.9 1069.27    11.9 1068.21    19.8 1068.56
    31.7 1072.26    47.6  1074.1  119.49 1071.99   130.8 1070.88  150.511060.775
  181.541059.704  194.111061.614  212.561061.715   277.5 1062.09   285.4 1059.94
   297.3 1053.35   305.7 1051.75   313.2 1051.36   320.7 1051.92   325.1 1053.73
   329.1 1056.96   341.1 1062.14     369 1081.36   408.9 1114.33   436.8 1134.29
   448.8 1140.15   484.7 1162.19   504.6 1177.06   532.6 1192.78   560.5 1211.64
#Mann= 9 ,-1 , 0
       0      .1       0    1.04     .12       0  119.49      .1       0
  150.51    .016       0  181.54     .12       0  194.11      .1       0
  212.56     .12       0   305.7    .045       0   320.7     .12       0
Bank Sta=305.7,320.7
XS Rating Curve= 0 ,0
Exp/Cntr=0.3,0.1

Type RM Length L Ch R = 1 ,3120.1  ,354.6,347.3,341.1
XS GIS Cut Line= 3
     1771594.295      323424.447     1771792.418      323389.104
     1772092.022      323324.952
#Sta/Elev= 30
       0 1073.23    15.8 1072.96    31.6 1067.52    41.71065.942    90.8 1067.02
  101.711064.735   106.5 1063.34   122.3 1063.34  131.711058.724     146 1049.17
   177.6 1047.69  191.711042.145  195.561041.058   205.2 1040.26  211.241040.943
  221.851049.433     241 1065.23   280.8 1104.15   288.8  1110.6   300.7 1117.17
   316.6 1129.88   332.6 1136.67   348.5 1148.06   364.4 1156.02   376.3 1165.08
   404.2 1183.06   428.1 1195.94   451.9 1212.37   491.7 1233.75   507.6 1240.44
#Mann= 8 ,-1 , 0
       0      .1       0    41.7     .12       0  101.71      .1       0
  131.71    .016       0  191.71      .1       0  195.56    .045       0
  211.24      .1       0  221.85     .12       0
Bank Sta=195.56,211.24
XS Rating Curve= 0 ,0
Exp/Cntr=0.3,0.1

Type RM Length L Ch R = 1 ,2772.8  ,473.2,461.5,449.7
XS GIS Cut Line= 3
     1771704.172      323813.831     1771784.069      323760.567
     1772208.005       323594.55
#Sta/Elev= 30
       0 1105.24      23 1088.97    38.4 1072.22    53.8 1062.05    59.31060.967
    69.1 1062.99     100 1062.28     116 1066.35     128 1064.54     136 1061.48
  158.361044.376   167.9 1040.11  190.081040.582   215.8 1041.52   227.8 1034.51
   243.3 1029.43   251.8 1029.02   258.3 1029.75   291.7  1033.8   319.7  1043.7
   331.6  1052.5   343.6 1058.21   359.6 1071.81   379.6 1084.39   399.6 1100.89
   411.5 1105.85   447.5 1133.02   475.4 1148.91   535.3 1190.32   551.3 1198.46
#Mann= 6 ,-1 , 0
       0      .1       0    59.3     .12       0  158.36    .016       0
  190.08      .1       0   243.3    .045       0   258.3     .12       0
Bank Sta=243.3,258.3
XS Rating Curve= 0 ,0
Exp/Cntr=0.3,0.1

Type RM Length L Ch R = 1 ,2311.3  ,457.9,454.9,451.4
XS GIS Cut Line= 2
     1772011.321      324214.741     1772427.814      323864.783
#Sta/Elev= 30
       0 1058.92    11.9  1058.2    23.8  1054.6    43.7 1042.16    55.6 1036.64
   87.651030.601    99.3  1028.1  111.931028.233     135 1028.87   146.9 1032.53
  157.841031.324   164.81031.735   178.7 1030.92   186.6 1026.63   190.5 1026.12
   202.5 1026.87  203.381026.979   214.4 1028.44   222.4 1031.82   353.4 1123.76
   373.3 1132.66   385.2 1142.34     405  1154.6   416.9 1165.05   432.8 1173.02
   448.7 1186.46   496.4 1214.78   512.2 1226.31   532.1 1231.17     544 1239.56
#Mann= 8 ,-1 , 0
       0     .12       0   87.65      .1       0  111.93    .016       0
  157.84     .04       0   164.8      .1       0   186.6    .045       0
   202.5      .1       0  203.38     .12       0
#XS Ineff= 2 , 0
          146.75 1034.63
Permanent Ineff=
       F       F
Bank Sta=186.6,202.5
XS Rating Curve= 0 ,0
Exp/Cntr=0.3,0.1

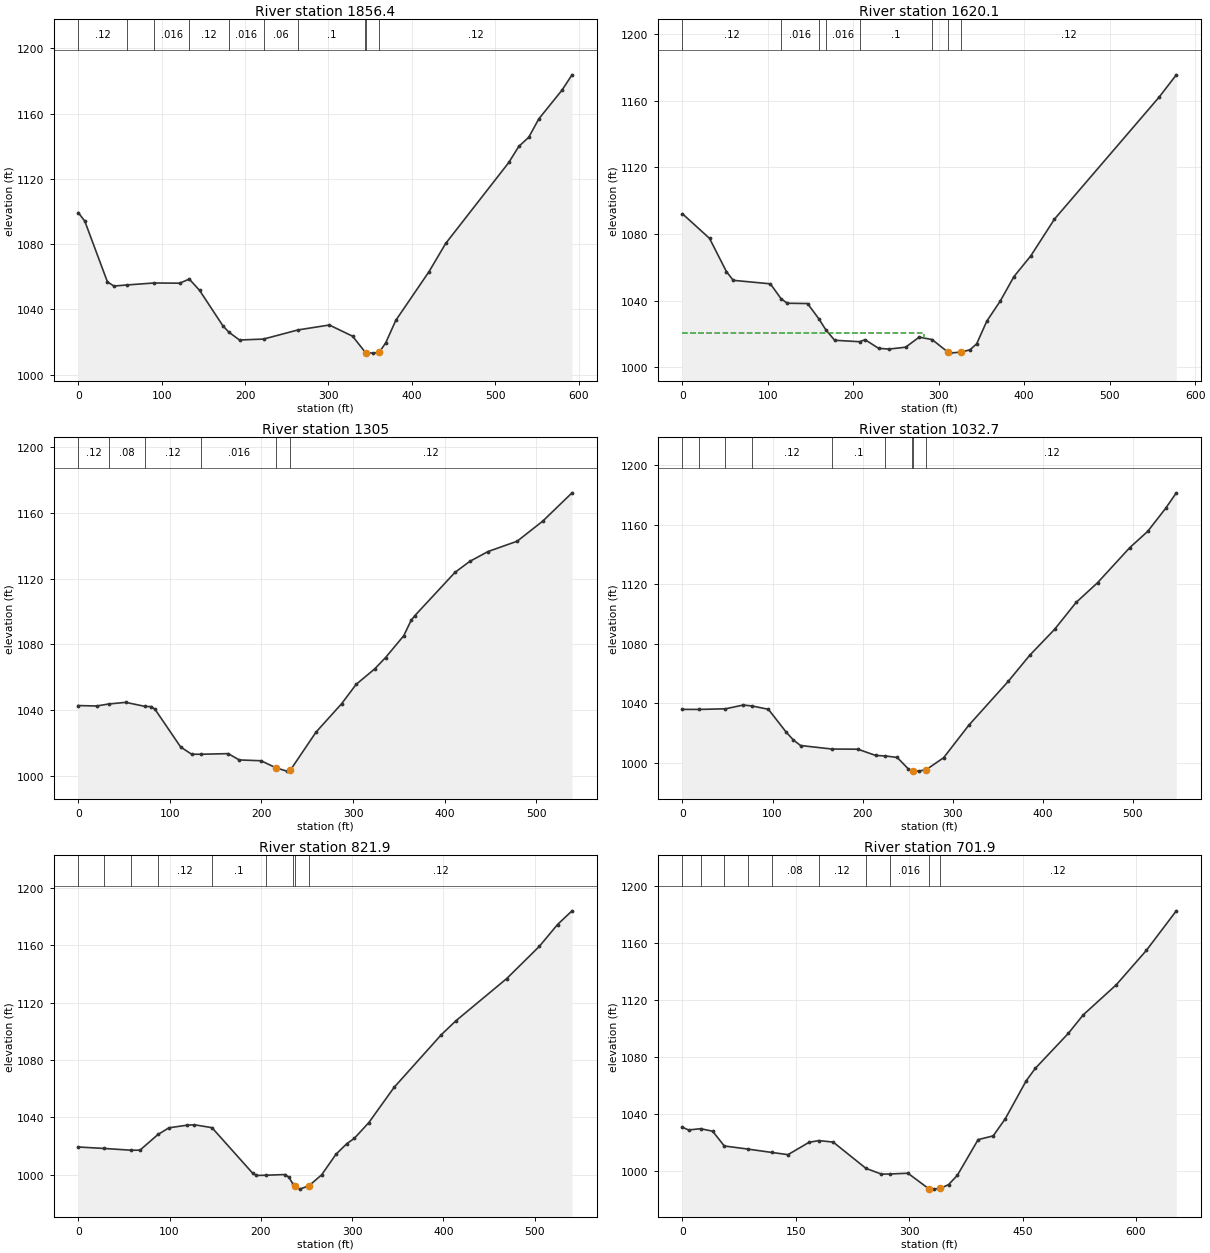
Type RM Length L Ch R = 1 ,1856.4  ,234.7,236.3,239.2
XS GIS Cut Line= 3
     1772352.932      324584.839     1772362.194      324503.623
     1772726.292      324146.205
#Sta/Elev= 30
       0 1099.34     7.8 1094.16      35 1056.84    42.8 1054.28   58.521054.954
   90.971056.166   121.6 1056.04  133.131058.551   145.5 1051.62   173.4 1029.92
  180.791025.895   193.4 1021.19  222.171021.767  263.561027.378     301 1030.38
   328.9 1023.53  343.961013.784   344.8 1013.48   352.8 1013.14   360.8 1013.58
   368.7 1019.51   380.7 1033.23   420.6 1063.17   440.5  1080.4   516.2 1130.08
   528.2 1139.95   540.1 1145.53   552.1 1156.76     580 1174.46     592 1183.82
#Mann= 10 ,-1 , 0
       0     .12       0   58.52      .1       0   90.97    .016       0
  133.13     .12       0  180.79    .016       0  222.17     .06       0
  263.56      .1       0  343.96     .12       0   344.8    .045       0
   360.8     .12       0
Bank Sta=344.8,360.8
XS Rating Curve= 0 ,0
Exp/Cntr=0.3,0.1

Type RM Length L Ch R = 1 ,1620.1  ,336.1,315.1,292.5
XS GIS Cut Line= 3
     1772485.455      324692.571     1772723.722      324478.166
     1772920.874      324312.504
#Sta/Elev= 30
       0 1092.15    31.7 1077.35    51.4 1057.43    59.4 1052.17   102.9 1050.06
  115.53    1041   122.7 1038.39   146.4 1038.21  159.681028.976  167.681022.505
   178.1 1016.13  207.411015.266   213.7 1016.47   229.5 1011.31   241.4 1010.82
   261.2 1011.96     277 1018.01  292.161016.563  310.641009.038   312.6  1008.4
  326.291009.053   336.4 1010.37   344.3 1013.96   356.2 1027.62     372 1039.76
   387.9 1054.37   407.7 1066.88   435.4 1088.97   558.2 1162.49     578  1175.7
#Mann= 8 ,-1 , 0
       0     .12       0  115.53    .016       0  159.68     .12       0
  167.68    .016       0  207.41      .1       0  292.16     .12       0
  310.64    .045       0  326.29     .12       0
#XS Ineff= 2 , 0
          282.97 1020.37
Permanent Ineff=
       F       F
Bank Sta=310.64,326.29
XS Rating Curve= 0 ,0
Exp/Cntr=0.3,0.1

Type RM Length L Ch R = 1 ,1305    ,280.9,272.4,264
XS GIS Cut Line= 2
     1772896.355      324892.368     1773043.721      324373.899
#Sta/Elev= 30
       0 1042.79      20 1042.52   33.35 1043.75    51.9 1044.74   73.121042.243
    79.8 1042.14    83.8 1040.52   111.8 1017.55   123.8 1013.14  134.531013.135
   163.7 1013.51   175.7 1009.67   199.6 1009.17   215.6 1004.91   227.6 1002.85
   231.6 1003.51   259.5 1026.57   287.5 1043.92   303.4 1055.74   323.4 1065.01
   335.4    1072   355.3 1085.32   363.3 1094.62   367.3  1097.5   411.2 1123.88
   427.2 1130.54   447.2 1136.58   479.1 1142.89   507.1 1155.16     539 1172.36
#Mann= 6 ,-1 , 0
       0     .12       0   33.35     .08       0   73.12     .12       0
  134.53    .016       0   215.6    .045       0   231.6     .12       0
Bank Sta=215.6,231.6
XS Rating Curve= 0 ,0
Exp/Cntr=0.3,0.1

Type RM Length L Ch R = 1 ,1032.7  ,210.7,210.8,210.4
XS GIS Cut Line= 2
     1773211.499       324958.31     1773240.495      324410.794
#Sta/Elev= 30
       0 1036.02   18.171035.988   47.751036.403    67.5 1038.94   77.331038.305
    95.4 1036.07   115.2 1020.71   123.2 1015.45   131.1 1011.78  166.06 1009.42
   194.7 1009.31   214.6 1005.11  225.221004.787   238.4 1003.78   250.3  996.36
  254.79994.9571   255.9  994.86   262.2   994.6   270.9  995.69     290 1003.62
   317.8 1025.32   361.6 1054.75   385.4 1072.22   413.2 1089.73     437 1107.72
   460.9    1121   496.6  1144.5   516.5  1155.4   536.4 1170.84   548.3 1181.28
#Mann= 9 ,-1 , 0
       0      .1       0   18.17    .016       0   47.75     .08       0
   77.33     .12       0  166.06      .1       0  225.22    .016       0
  254.79     .12       0   255.9    .045       0   270.9     .12       0
Bank Sta=255.9,270.9
XS Rating Curve= 0 ,0
Exp/Cntr=0.3,0.1

Type RM Length L Ch R = 1 ,821.9   ,74.2,120,147.5
XS GIS Cut Line= 2
     1773422.625      324938.779      1773449.61      324398.565
#Sta/Elev= 30
       0 1019.26    28.21018.254   57.771017.026    67.6 1017.03   87.341027.999
    99.4 1032.66   119.3  1034.5   127.3 1034.76  146.491032.757   190.9 1001.08
   194.9   999.4  205.64 999.562   226.7 1000.04   230.7  998.14  235.21993.4833
  237.28991.8012   242.6  989.86  252.62992.1796   266.5  999.75   282.4 1014.25
   294.3 1021.65   302.3 1025.23   318.2 1036.21     346 1060.89   397.7 1097.63
   413.6  1107.3   469.3 1136.79   505.1  1159.3     525 1174.53   540.9 1184.08
#Mann= 9 ,-1 , 0
       0    .016       0    28.2     .06       0   57.77     .08       0
   87.34     .12       0  146.49      .1       0  205.64    .016       0
  235.21     .12       0  237.28    .045       0  252.62     .12       0
Bank Sta=237.28,252.62
XS Rating Curve= 0 ,0
Exp/Cntr=0.3,0.1

Type RM Length L Ch R = 1 ,701.9   ,41.2,36.5,28.3
XS GIS Cut Line= 4
     1773416.722      324992.425     1773507.694      324728.536
     1773582.694      324682.008        1773568.      324396.361
#Sta/Elev= 30
       0 1030.98       8  1029.1   24.051029.987    39.9 1028.22   55.291017.868
   86.531015.681  117.78 1013.35   139.6 1011.76   167.5 1020.44  180.261021.642
   199.4 1020.59  242.751002.148   263.2  998.12  273.99998.1759   298.3  998.74
   325.8  987.87   332.8  987.57   340.8  988.04     352   990.7   363.6  997.21
   391.2 1022.33   411.1 1024.94     427 1036.88   454.8 1063.62   466.7 1072.27
   510.4 1096.83   530.3  1109.9     574 1131.02   613.7 1155.08   653.4 1182.92
#Mann= 10 ,-1 , 0
       0     .12       0   24.05     .06       0   55.29    .016       0
   86.53     .06       0  117.78     .08       0  180.26     .12       0
  242.75      .1       0  273.99    .016       0   325.8    .045       0
   340.8     .12       0
Bank Sta=325.8,340.8
XS Rating Curve= 0 ,0
Exp/Cntr=0.3,0.1

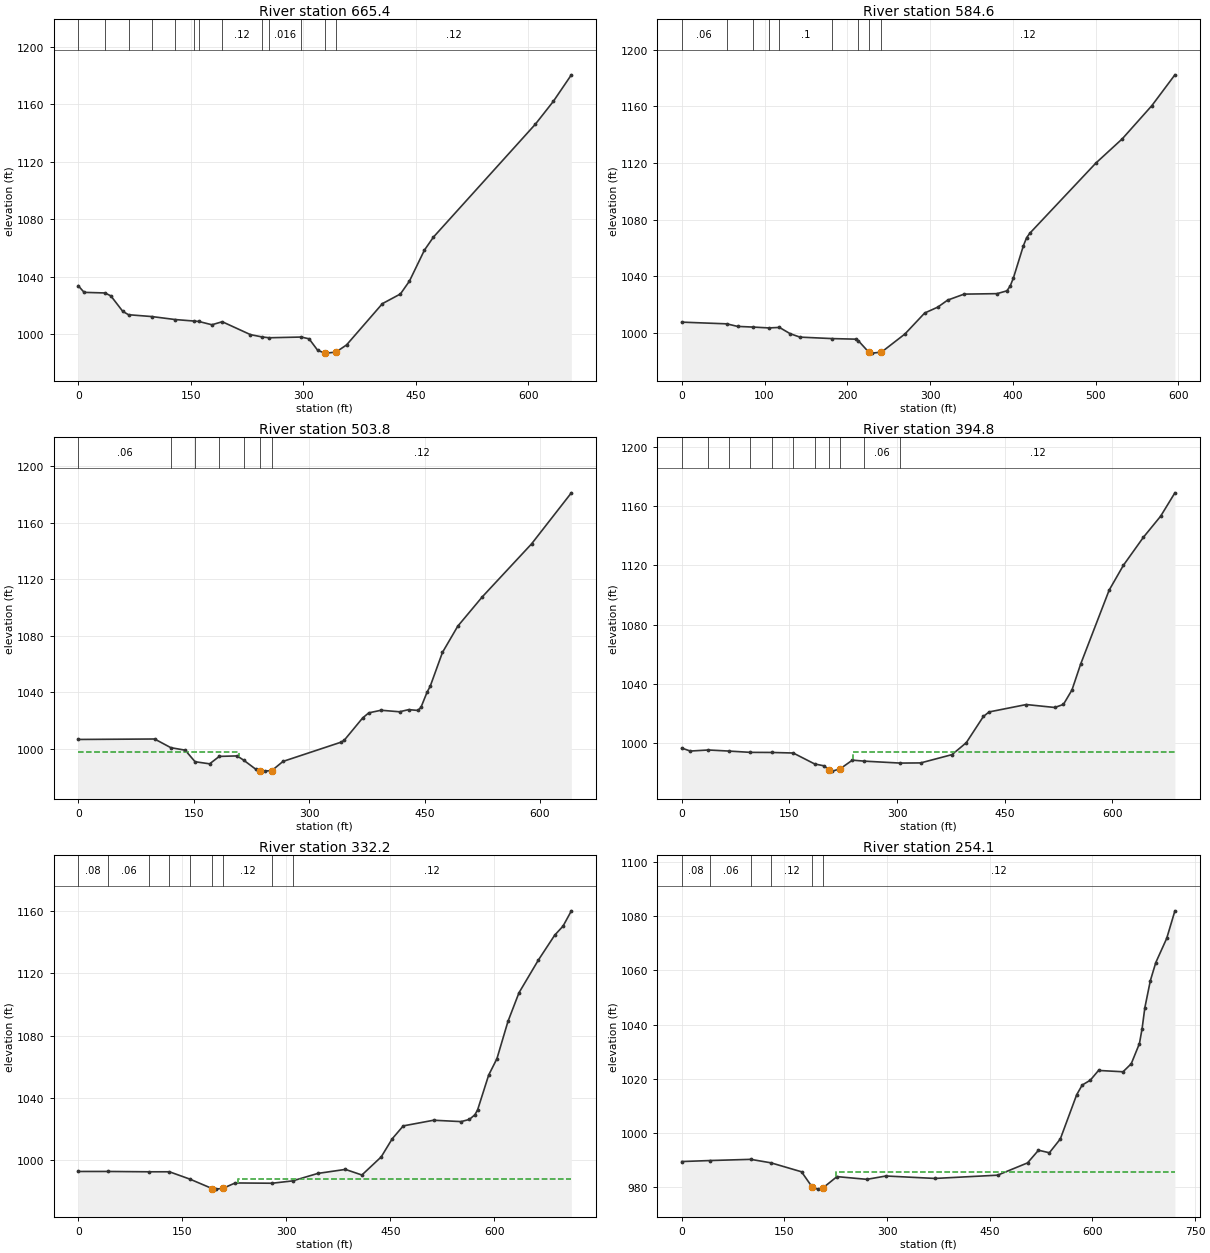
Type RM Length L Ch R = 1 ,665.4   ,109.4,80.8,73.8
XS GIS Cut Line= 4
     1773445.889      325003.536     1773534.777      324745.203
     1773609.777      324698.675     1773595.084      324403.306
#Sta/Elev= 30
       0  1033.7     7.9 1029.05    35.8 1028.63    43.6 1026.55    59.4 1015.82
   67.031013.486   98.271012.196   129.51010.111  154.631009.071  160.741008.782
   178.2  1006.5  191.981008.601   229.6  999.61  245.39997.9907  254.45997.4515
  297.31997.9458   307.7   996.7   319.2  988.67   328.6   986.8   330.8  986.75
   343.6   987.5   357.6  992.45   405.4  1021.2   429.4 1027.93   441.4 1036.88
   461.4 1058.46   473.4 1067.51   609.2 1146.09   633.2 1162.02   657.2 1180.47
#Mann= 13 ,-1 , 0
       0     .12       0    35.8     .06       0   67.03    .016       0
   98.27     .06       0   129.5     .08       0  154.63     .06       0
  160.74     .08       0  191.98     .12       0  245.39      .1       0
  254.45    .016       0  297.31     .12       0   328.6    .045       0
   343.6     .12       0
Bank Sta=328.6,343.6
XS Rating Curve= 0 ,0
Exp/Cntr=0.3,0.1

Type RM Length L Ch R = 1 ,584.6   ,81.7,80.7,79.5
XS GIS Cut Line= 3
     1773575.258       324961.11     1773697.654      324655.554
     1773615.223      324401.917
#Sta/Elev= 30
       0 1007.56    54.41006.352    67.4 1004.55   86.221004.073  105.111003.475
  118.041003.826   130.9  999.42   142.8  996.98  181.67995.9424   210.2  995.54
  213.49994.3474   226.3  986.13     230  985.68   241.3  986.38   269.7  999.22
   293.5    1014   309.3 1018.15   321.2 1023.09   341.1 1027.33   380.9 1027.67
   392.8 1029.65   396.8 1033.02   400.8 1038.95   412.8 1061.57   416.7 1067.22
   420.7 1070.44   500.3 1119.84   532.2 1136.95     568 1160.43   595.8 1182.14
#Mann= 9 ,-1 , 0
       0     .06       0    54.4    .016       0   86.22     .06       0
  105.11    .016       0  118.04      .1       0  181.67    .016       0
  213.49     .12       0   226.3    .045       0   241.3     .12       0
Bank Sta=226.3,241.3
XS Rating Curve= 0 ,0
Exp/Cntr=0.3,0.1

Type RM Length L Ch R = 1 ,503.8   ,117.1,109.1,101
XS GIS Cut Line= 3
     1773655.987      324994.096     1773762.758      324703.297
       1773630.5      324399.833
#Sta/Elev= 30
       0 1006.64    99.3 1006.96  120.411000.817     139  999.06  151.87990.8878
   170.8   989.4  183.34994.6632   206.5     995   214.8992.0716   230.4  985.72
   236.7  984.39   242.3  984.24   251.7  984.68   266.1   991.1   341.7 1004.74
   345.7  1006.1   369.6 1021.84   377.6 1025.46   393.5 1027.29   417.5 1026.22
   429.4 1027.73   441.4 1027.16   445.4 1029.38   453.4 1040.18   457.4 1044.27
   473.3  1068.2   493.2 1086.76   525.2 1107.58     589  1144.9   640.8 1181.06
#Mann= 7 ,-1 , 0
       0     .06       0  120.41    .016       0  151.87      .1       0
  183.34    .016       0   214.8     .12       0   236.7    .045       0
   251.7     .12       0
#XS Ineff= 2 , 0
          208.77  997.72
Permanent Ineff=
       F       F
Bank Sta=236.7,251.7
XS Rating Curve= 0 ,0
Exp/Cntr=0.3,0.1

Type RM Length L Ch R = 1 ,394.8   ,65.5,62.6,59.6
XS GIS Cut Line= 3
     1773816.041      325005.432     1773867.306      324632.472
     1773672.167      324390.806
#Sta/Elev= 30
       0  996.82    11.9  994.79   37.17995.5034   65.91994.7708   95.73993.9011
  125.54993.8422  155.35993.4666  185.17986.0872   198.1  984.83   205.7  981.98
     210  981.25   220.7  982.81   237.8  988.67  253.99987.9932  304.42986.6774
   332.9  986.79   376.5  992.37   396.4  1000.4   420.3 1018.13   428.2 1021.16
     480 1026.15   519.8 1024.17   531.8 1026.26   543.7    1036   555.7 1053.32
   595.5 1103.32   615.4 1120.11   643.3 1139.01   667.2 1153.16   687.1 1168.93
#Mann= 11 ,-1 , 0
       0      .1       0   37.17     .12       0   65.91      .1       0
   95.73     .06       0  125.54    .016       0  155.35     .08       0
  185.17     .12       0   205.7    .045       0   220.7     .12       0
  253.99     .06       0  304.42     .12       0
#XS Ineff= 2 , 0
                          238.39          993.92
Permanent Ineff=
       F       F
Bank Sta=205.7,220.7
XS Rating Curve= 0 ,0
Exp/Cntr=0.3,0.1

Type RM Length L Ch R = 1 ,332.2   ,77.8,78.1,78.2
XS GIS Cut Line= 3
     1773893.834      325012.325     1773915.536      324647.742
     1773685.501      324389.929
#Sta/Elev= 30
       0  992.37   42.73992.3821  101.91992.1642   131.5992.1688  161.09987.4204
  192.95981.3765   198.5  980.99  208.71981.5206   226.3  984.97  279.44984.7923
  309.03986.2961   345.4  991.12   385.1   993.7   408.9   990.1   436.7 1001.75
   452.6 1013.45   468.5 1021.75   512.2  1025.4   551.9 1024.52   563.8 1025.93
   571.8 1028.94   575.7 1032.13   591.6 1054.51   603.5 1065.06   619.4 1089.09
   635.3 1107.58   663.1 1128.56   686.9 1144.77   698.8 1150.54   710.8 1160.39
#Mann= 9 ,-1 , 0
       0     .08       0   42.73     .06       0  101.91    .016       0
   131.5     .08       0  161.09     .12       0  192.95    .045       0
  208.71     .12       0  279.44     .06       0  309.03     .12       0
#XS Ineff= 2 , 0
                          230.19           987.5
Permanent Ineff=
       F       F
Bank Sta=192.95,208.71
XS Rating Curve= 0 ,0
Exp/Cntr=0.3,0.1

Type RM Length L Ch R = 1 ,254.1   ,52.1,53,53.8
XS GIS Cut Line= 3
     1773970.927      325011.131     1774002.394       324522.85
     1773824.443      324375.281
#Sta/Elev= 30
       0  989.56   41.55989.9306  100.75 990.367  130.35989.0849     175  985.78
   190.9  980.04   198.9  979.39   206.9  979.97   226.8     984   270.5     983
   298.4  984.23     370  983.33   461.4  984.53   505.2  989.06   521.2  993.73
   537.1   992.8   553.1  997.89     577 1014.18     585 1017.74   596.9 1019.55
   608.9 1023.14   644.7 1022.65   656.7  1025.6   668.7 1033.07   672.6  1038.6
   676.6 1046.29   684.6 1056.22   692.6 1062.93   708.5 1071.82   720.5 1081.98
#Mann= 6 ,-1 , 0
       0     .08       0   41.55     .06       0  100.75    .016       0
  130.35     .12       0   190.9    .045       0   206.9     .12       0
#XS Ineff= 2 , 0
                          225.21          985.67
Permanent Ineff=
       F       F
Bank Sta=190.9,206.9
XS Rating Curve= 0 ,0
Exp/Cntr=0.3,0.1