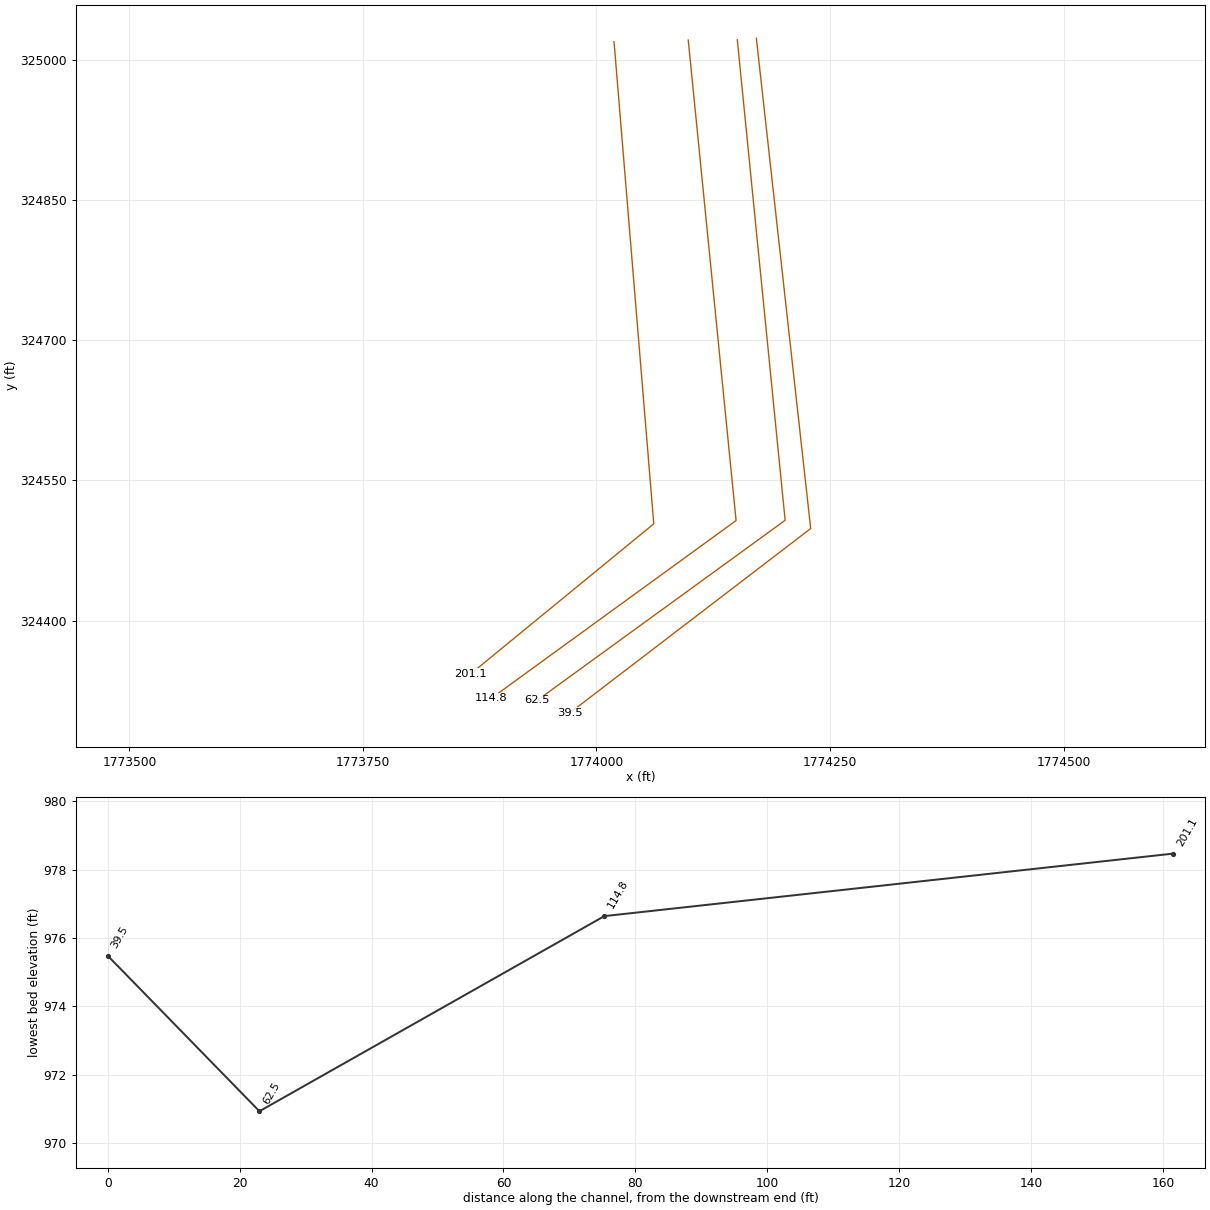
HEC-RAS study COWCK.prj: COWCK

--- COWCK.g01 (geometry) --- (continued)

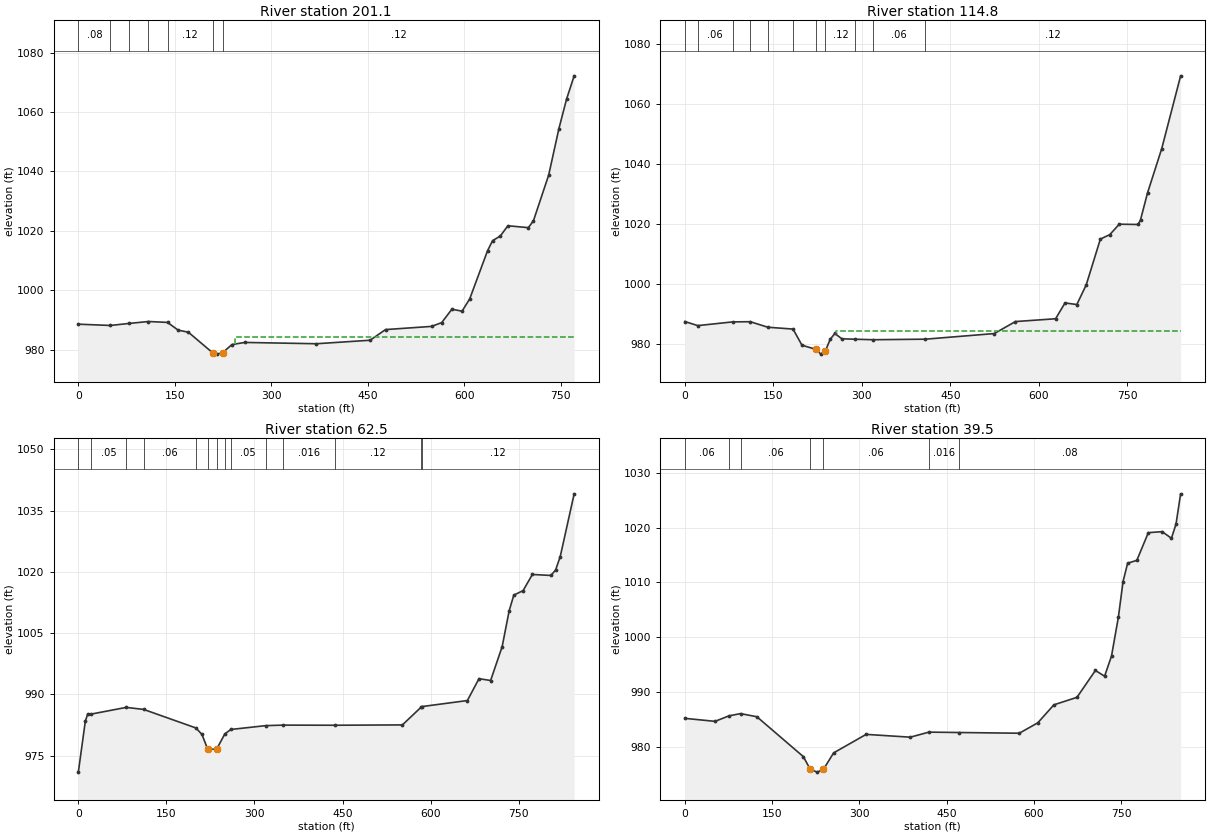
Type RM Length L Ch R = 1 ,201.1   ,85.5,86.3,86.7
XS GIS Cut Line= 3
     1774018.834       325019.27     1774061.369      324503.645
     1773865.188      324343.054
#Sta/Elev= 30
       0  988.56   49.78988.1266   79.41988.8243  109.05  989.46  138.69989.1542
   155.2  986.55   171.1  985.85   209.3  978.84   214.9  978.47   224.3  978.96
   238.8  981.69   258.7  982.41   370.1  981.97   453.7  983.15   477.6  986.74
   549.1  987.81   564.9  989.08   580.8   993.6   596.6  992.94   608.5  997.09
   636.2 1013.28   644.1 1016.71     656 1018.24   667.9 1021.72   699.6 1021.08
   707.5 1023.34   731.3  1038.8   747.1 1054.36     759 1064.33   770.9 1072.23
#Mann= 7 ,-1 , 0
       0     .08       0   49.78     .06       0   79.41     .08       0
  109.05    .016       0  138.69     .12       0   209.3    .045       0
   224.3     .12       0
#XS Ineff= 2 , 0
                          242.85          984.29
Permanent Ineff=
       F       F
Bank Sta=209.3,224.3
XS Rating Curve= 0 ,0
Exp/Cntr=0.3,0.1

Type RM Length L Ch R = 1 ,114.8   ,52.4,52.3,52.3
XS GIS Cut Line= 3
     1774098.266      325021.053     1774149.481      324507.164
     1773887.359      324316.997
#Sta/Elev= 30
       0  987.49   21.97986.1312   81.33 987.369  111.01987.4268   140.7985.5903
  183.44984.9769   198.6   979.6   222.5  978.22   230.4  976.64   238.4  977.79
   246.3  981.52   254.2  983.52   266.2  981.74  289.11981.6011  318.79981.4324
  407.84981.6164   524.4  983.48   560.4  987.48   628.4  988.41   644.4  993.68
   664.4  993.14   680.4  999.73   704.3 1014.93   720.3 1016.41   736.3 1019.88
   768.3 1019.78   772.3 1021.32   784.3 1030.34   808.3 1045.04   840.3 1069.25
#Mann= 11 ,-1 , 0
       0     .08       0   21.97     .06       0   81.33    .016       0
  111.01     .08       0   140.7     .12       0  183.44    .016       0
   222.5    .045       0   238.4     .12       0  289.11     .08       0
  318.79     .06       0  407.84     .12       0
#XS Ineff= 2 , 0
                          256.64          984.29
Permanent Ineff=
       F       F
Bank Sta=222.5,238.4
XS Rating Curve= 0 ,0
Exp/Cntr=0.3,0.1

Type RM Length L Ch R = 1 ,62.5    ,22.6,23,23.4
XS GIS Cut Line= 3
     1774150.782      325021.327     1774201.998      324507.438
     1773936.373      324314.729
#Sta/Elev= 30
       0  970.93    11.9  983.39    15.9  985.14   22.24  985.16   81.61986.7913
  111.29986.2948  200.34981.7499   210.6  980.16  220.33976.5614  235.45976.5292
  249.52 980.284  259.71981.3802  319.07982.3195  348.75982.4485   437.8  982.42
     552   982.5  584.38986.9066  585.65986.9987   662.7  988.47   682.5  993.83
   702.3  993.38     722  1001.7   733.9 1010.48   741.8  1014.3   757.6  1015.4
   773.4 1019.36   805.1 1019.12     813 1020.46   820.9 1023.75   844.6 1039.12
#Mann= 14 ,-1 , 0
       0     .06       0   22.24     .05       0   81.61    .016       0
  111.29     .06       0  200.34    .016       0  220.33    .045       0
  235.45    .016       0  249.52     .12       0  259.71     .05       0
  319.07     .06       0  348.75    .016       0   437.8     .12       0
  584.38    .016       0  585.65     .12       0
Bank Sta=220.33,235.45
XS Rating Curve= 0 ,0
Exp/Cntr=0.3,0.1

Type RM Length L Ch R = 1 ,39.5    ,40,39.5,39.1
XS GIS Cut Line= 3
     1774171.189       325022.91     1774229.349      324498.604
     1773971.329      324301.351
#Sta/Elev= 30
       0  985.27      52  984.72    75.9  985.72    95.9  986.13   123.9  985.56
   203.8   978.3   215.8  975.96   227.8  975.48   238.4975.9945   255.8  978.98
   311.7  982.35   387.6  981.84   419.6  982.76   471.6  982.69     575  982.56
   606.7  984.45   634.5  987.73   674.1  989.09   705.8  993.98   721.6  992.94
   733.5  996.61   745.4 1003.74   753.3 1010.15   761.2  1013.5     777 1014.02
   796.8 1019.06   820.6 1019.25   836.5 1018.04   844.4 1020.63   852.3 1026.13
#Mann= 7 ,-1 , 0
       0     .06       0    75.9    .016       0    95.9     .06       0
   215.8    .045       0   238.4     .06       0   419.6    .016       0
   471.6     .08       0
#XS Ineff= 2 , 0
          195.05  976.28  275.54          976.49
Permanent Ineff=
       F       F
Bank Sta=215.8,238.4
XS Rating Curve= 0 ,0
Exp/Cntr=0.3,0.1

Chan Stop Cuts=-1
Use User Specified Reach Order=0
Composite Channel Slope=5